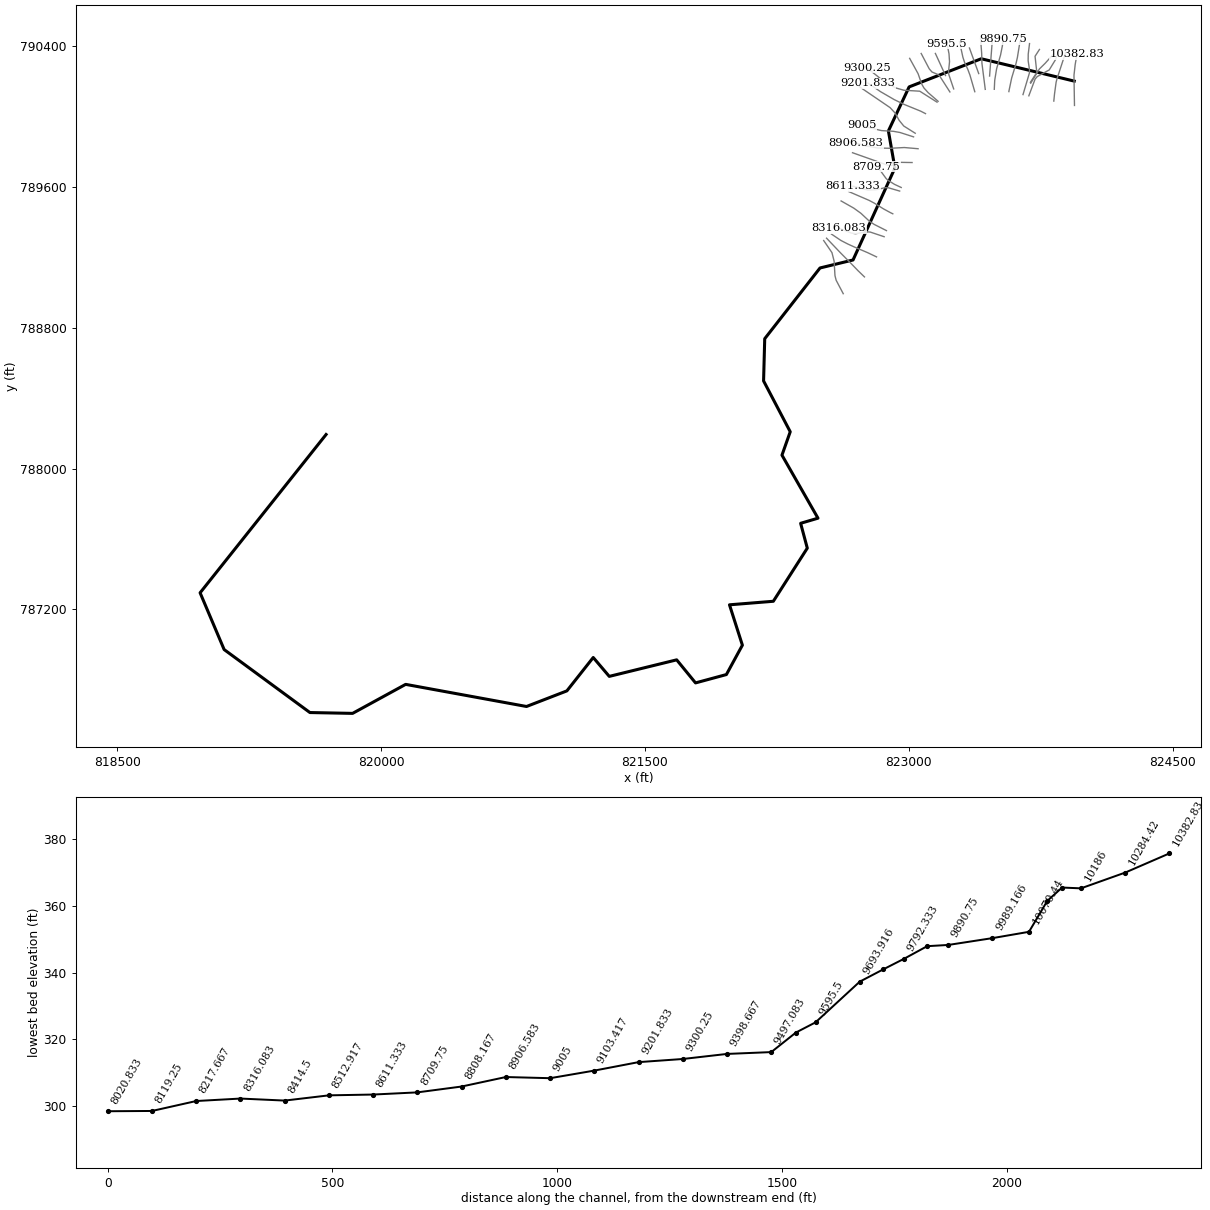
--- 17397_ras.prj (project) ---

Proj Title=17397
Current Plan=p01
Default Exp/Contr=0.3,0.1
English Units
Geom File=g01
Flow File=f01
Plan File=p01
Y Axis Title=Elevation
X Axis Title(PF)=Main Channel Distance
X Axis Title(XS)=Station
BEGIN DESCRIPTION:
RFD model 17397 exported to HEC-RAS
END DESCRIPTION:

--- 17397_ras.p01 (plan) ---

Plan Title=Plan 01
Program Version=4.10
Short Identifier=Plan 01
Geom File=g01
Flow File=f01
Subcritical Flow
Calc Critical at every XS
Secant Critical Depth

--- 17397_ras.f01 (steady flow) ---

Flow Title=Flow 01
Program Version=5.01
Number of Profiles= 6
Profile Names=10yr,25yr,50yr,100yr,100plus,500yr
River Rch & RM=17397,67,10382.83
  280.94   446.1  599.48  737.77 1077.14 1726.69
River Rch & RM=17397,67,10284.42
  284.93  452.54  608.24  748.66 1093.04 1749.07
River Rch & RM=17397,67,   10186
  286.01  454.28  610.62  751.61 1097.36 1755.15
River Rch & RM=17397,67,10111.14
  292.27  464.35  624.26  768.51 1122.02 1789.46
River Rch & RM=17397,67,9989.166
  294.82  468.46  629.83  775.42 1132.11 1803.51
River Rch & RM=17397,67, 9890.75
     297  471.96   634.6  781.33 1140.74 1815.53
River Rch & RM=17397,67,9792.333
  299.21  475.51   639.4  787.27 1149.41 1827.51
River Rch & RM=17397,67,9693.916
  302.09  480.15  645.71  795.11 1160.86 1843.43
River Rch & RM=17397,67,9551.869
  303.84     483  649.59  799.95 1167.92 1853.36
River Rch & RM=17397,67,9398.667
  309.39  492.03  661.94  815.36 1190.42 1884.98
River Rch & RM=17397,67,9201.833
  310.75  494.26  664.99  819.18    1196 1892.86
River Rch & RM=17397,67,9103.417
  313.46   498.7  671.09   826.8 1207.13 1908.57
River Rch & RM=17397,67,    9005
  314.82  500.92  674.13  830.61 1212.68  1916.4
River Rch & RM=17397,67,8906.583
   318.2  506.46  681.72  840.11 1226.55 1935.93
River Rch & RM=17397,67,8808.167
  319.89  509.22  685.51  844.85 1233.48 1945.67
River Rch & RM=17397,67,8611.333
   339.3   540.7  728.43  898.28 1311.48 2053.47
River Rch & RM=17397,67,8512.917
   342.3   545.6  735.16  906.69 1323.77 2070.59
River Rch & RM=17397,67,  8414.5
  343.96  548.32  738.89  911.36 1330.59 2080.07
River Rch & RM=17397,67,8316.083
  344.96  549.95  741.13  914.16 1334.68 2085.75
River Rch & RM=17397,67, 8119.25
  345.62  551.04  742.62  916.03  1337.4 2089.54
River Rch & RM=17397,67,8020.833
  348.94  556.47  750.06  925.34    1351 2108.43
River Rch & RM=17397,67,    7824
  352.58  562.43  758.23  935.57 1365.93 2129.12
River Rch & RM=17397,67,7627.167
  353.56  564.04  760.45  938.34 1369.98 2134.75
River Rch & RM=17397,67, 7528.75
  361.45  576.96  778.18  960.54 1402.39  2179.6
River Rch & RM=17397,67,7430.333
  362.75  579.09   781.1  964.21 1407.74 2187.03
River Rch & RM=17397,67,7331.917
  364.04  581.21  784.03  967.88  1413.1 2194.46
River Rch & RM=17397,67,7135.083
  389.51  622.87  841.14 1039.32 1517.41 2337.41
River Rch & RM=17397,67,7036.667
  392.05  627.05   846.9 1046.54 1527.96 2351.88
River Rch & RM=17397,67, 6938.25
  393.96  630.19  851.21 1051.95 1535.85 2362.71
River Rch & RM=17397,67,6741.417
  397.45  635.93  859.11 1061.86 1550.31  2382.5
River Rch & RM=17397,67,    6643
  398.72  638.01  861.98 1065.45 1555.56 2389.69
River Rch & RM=17397,67,6544.583
  400.94  641.66  866.99 1071.74 1564.74 2402.24
River Rch & RM=17397,67, 6347.75
  401.89  643.22  869.14 1074.44 1568.68 2407.61
River Rch & RM=17397,67,6150.917
  402.84  644.78  871.28 1077.13  1572.6 2412.98
River Rch & RM=17397,67,  6052.5
   454.3  728.81   986.4 1220.99 1782.65 2694.53
River Rch & RM=17397,67,5954.083
  456.77  732.86  991.97 1227.98 1792.86 2708.21
River Rch & RM=17397,67, 5757.25
   458.3  735.38  995.44 1232.34 1799.22 2716.75
River Rch & RM=17397,67,5658.833
  459.52  737.39  998.21 1235.82  1804.3 2723.57
River Rch & RM=17397,67,5560.417
  461.66  740.91 1003.06 1241.91 1813.18  2735.5
River Rch & RM=17397,67,5363.583
  497.22  799.54 1083.89 1343.47 1961.47 2933.55
River Rch & RM=17397,67, 5166.75
  497.82  800.53 1085.25 1345.18 1963.97 2936.87
River Rch & RM=17397,67,5068.333
  498.42  801.52 1086.61 1346.89 1966.46 2940.18
Boundary for River Rch & Prof#=17397,67,1
Up Type= 0
Dn Type= 2
Boundary for River Rch & Prof#=17397,67,2
Up Type= 0
Dn Type= 2
Boundary for River Rch & Prof#=17397,67,2
Up Type= 0
Dn Type= 2
Boundary for River Rch & Prof#=17397,67,2
Up Type= 0
Dn Type= 2
Boundary for River Rch & Prof#=17397,67,2
Up Type= 0
Dn Type= 2
Boundary for River Rch & Prof#=17397,67,2
Up Type= 0
Dn Type= 2

--- 17397_ras.g01 (geometry) ---

Geom Title=17397
Program Version=4.10

River Reach=17397,67
Reach XY= 30
823939.888318778790201.849497858823411.421114804790328.896401665
823001.481875151790168.987746735822883.629455655789918.587458975
822920.603220197789707.748331626822682.644676299789185.189002446
822494.950413288789139.749091977822180.679068298788737.666635931
822174.208775907788497.803653522 822325.69117156788208.799434336
822278.742864075788075.896628329822483.396319687787717.671255995
822384.803364784787688.510837611822422.673553228787547.299511548
822229.621346536787245.386842107821980.421089828787225.299780848
 822053.77932373786995.894557883821962.801020293786828.862589513
821787.451899768786781.425695484821680.291862608786912.467418443
821297.176484944786818.495092036821205.981922421786925.785795478
821056.190879285786736.051562732820826.835669252786647.357004069
820139.807243944786773.105475088819838.330942452786608.235622695
819595.736731112786612.946189922819108.193024813786970.949297925
818971.586575748787293.623151843819687.654876561788193.269092558

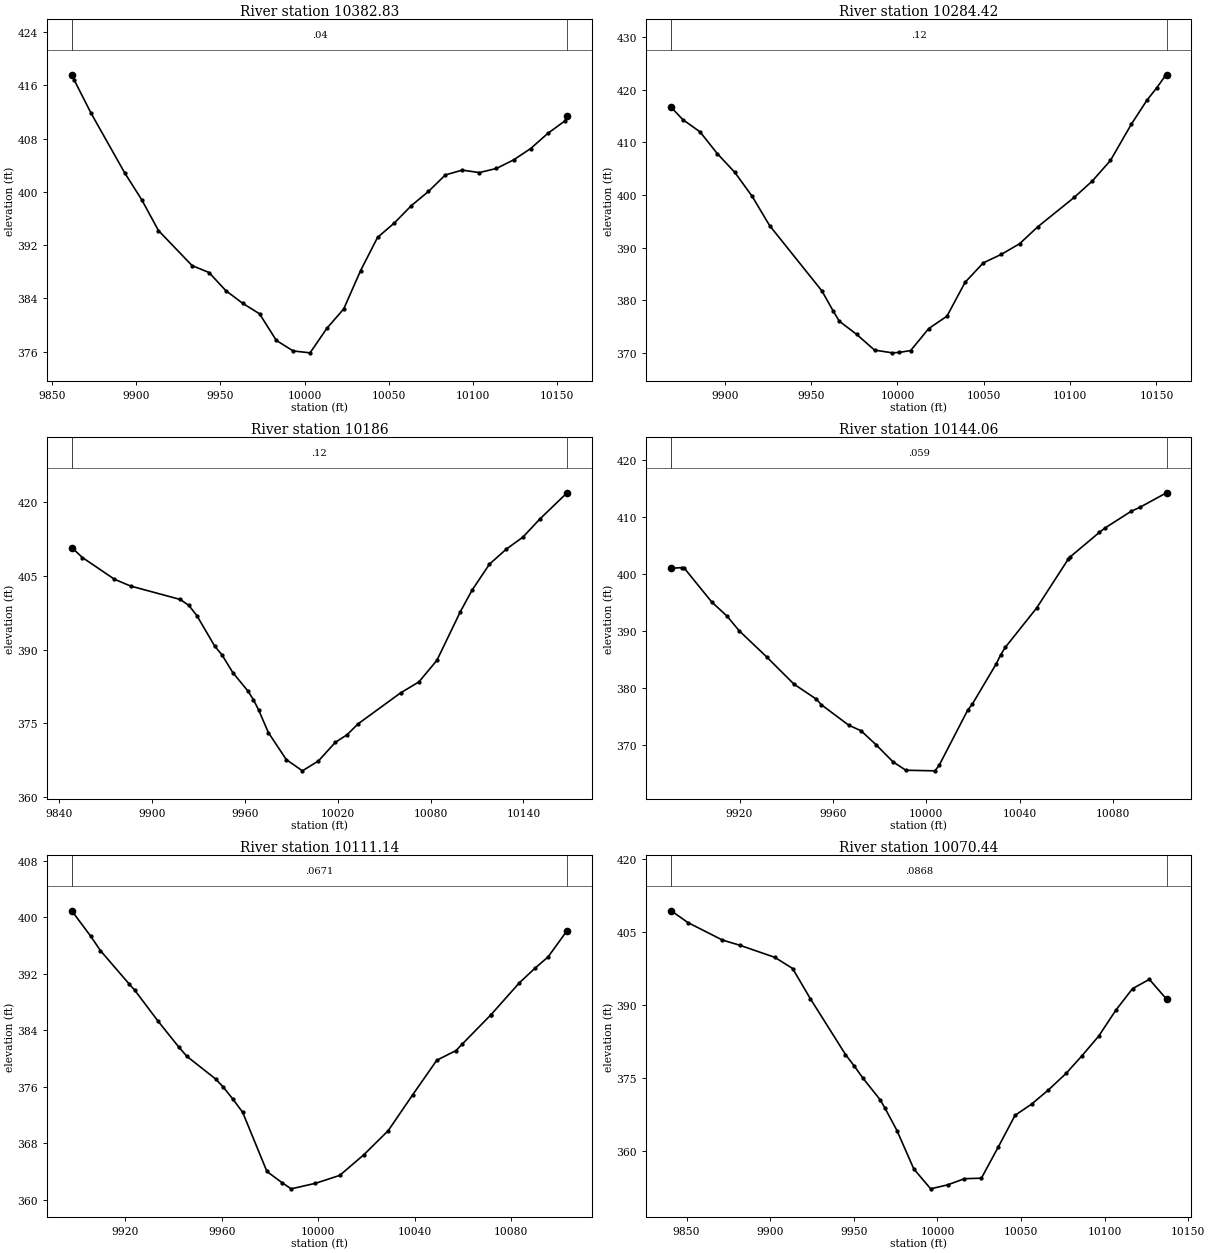
Type RM Length L Ch R = 1 ,10382.83,98.416700,98.416700,98.416700
XS GIS Cut Line= 6
823941.231885167790063.514626812823938.967210468790200.776390462
823938.815211382790202.770606167823938.506047366790236.239441864
823945.530644417 790297.87787954823955.905958041790356.313700061
#Sta/Elev= 30
 9861.72417.59159863.205416.78789873.206411.81039893.209402.83239903.211398.8442
9913.212 394.1829933.215388.91349943.216387.88379953.217385.15729963.219 383.257
 9973.22381.67819983.221377.67249993.223376.096710003.23375.812710013.23379.5036
10023.23382.418510033.23388.165510043.29 393.15210053.35 395.34210063.42397.9402
10073.48400.054310083.55402.540810093.61403.268410103.74402.8966 10113.9403.5183
10124.05404.798210134.21406.506710144.37408.779210154.52410.657410155.86411.4302
#Mann= 3 , 0 , 0
 9861.72    0.04       0 9861.72    0.04       010155.86    0.04       0
#XS Ineff= 2 , 0
       0                               0
Bank Sta=9861.72,10155.86
Exp/Cntr=0.3,0.1

Type RM Length L Ch R = 1 ,10284.42,98.416600,98.416600,98.416600
XS GIS Cut Line= 6
823823.757133242790088.329518233823827.877013696790129.273321377
823836.787251019790194.674770489823841.248132904790212.885905137
823889.595625467790360.515279294 823891.03401896790365.948146456
#Sta/Elev= 30
 9868.98416.66379875.684414.33239885.735411.97889895.785407.83349905.836404.3055
 9915.91399.74679926.002394.2062 9956.28381.80599962.896377.94799966.372376.0587
9976.471373.53519986.767370.56819997.114370.0515   10001370.131310007.65370.4799
10018.17374.665910028.69377.003710039.22383.445910049.74387.123610060.26388.7559
10070.78390.7629 10081.3393.977210102.34399.537910112.86402.660410123.39 406.566
10135.45413.431110144.43417.964710150.23420.376410154.87422.505710155.85422.8271
#Mann= 3 , 0 , 0
 9868.98    0.12       0 9868.98    0.12       010155.85    0.12       0
#XS Ineff= 2 , 0
       0                               0
Bank Sta=9868.98,10155.85
Exp/Cntr=0.3,0.1

Type RM Length L Ch R = 1 ,   10186,41.935000,41.935000,41.935000
XS GIS Cut Line= 6
823681.817292892790118.312315974823717.651076221790213.781647053
823729.713247115790227.597843531823797.849780195790265.564064723
823832.768555397790322.696673471823851.766278573790371.779989086
#Sta/Elev= 30
9848.184 410.7559855.105408.71719875.804404.30069886.154402.9272 9918.26400.1932
 9923.77399.00229929.022396.90999940.526390.71129945.265388.90899952.246385.3168
9961.803381.64399965.521379.83199968.969377.68749975.217373.11699986.796367.6088
9997.241365.321910007.58367.3413 10018.5371.125610026.11 372.67610033.25374.8953
 10060.7381.192910072.45383.407510084.09387.792110099.25397.701810106.83402.0852
10118.07407.372110128.89410.4175 10139.7412.878910150.52416.530610168.24421.8993
#Mann= 3 , 0 , 0
9848.184    0.12       09848.184    0.12       010168.24    0.12       0
#XS Ineff= 2 , 0
       0                               0
Bank Sta=9848.184,10168.24
Exp/Cntr=0.3,0.1

Type RM Length L Ch R = 1 ,10144.06,32.927100,32.927100,32.927100
XS GIS Cut Line= 4
823692.513943821790190.145234555823742.137082875790271.125326484
823773.798472166790302.177842915823822.508301914790356.367528498
#Sta/Elev= 30
9890.705400.99149895.463401.11739896.398400.97719908.126 395.0829914.602392.6412
9919.855390.06199931.583385.50559943.311380.7293 9952.88378.10959955.039377.1273
9966.767373.5476 9972.02372.58049978.496370.12149985.679367.15889991.213365.6715
 10003.7365.564210005.49366.5262 10017.7376.155510019.78377.287210030.03 384.332
10031.82385.837910033.82387.156110047.27394.054910060.71402.542210061.74403.0284
10074.16407.2844 10076.7408.075710087.61410.928510091.66411.696410102.89414.1991
#Mann= 3 , 0 , 0
9890.705   0.059       09890.705   0.059       010102.89   0.059       0
#XS Ineff= 2 , 0
       0                               0
Bank Sta=9890.705,10102.89
Exp/Cntr=0.3,0.1

Type RM Length L Ch R = 1 ,10111.14,40.697700,40.697700,40.697700
XS GIS Cut Line= 4
823690.687325239 790195.01621753823727.219697475790251.032521725
 823717.17329511790342.972325325823742.137082875790381.635752663
#Sta/Elev= 29
9897.794400.90899905.689 397.2969909.713395.25979921.652390.52849923.995389.6312
9933.591385.28219942.301381.56959945.529380.31229957.468377.09649960.607375.9612
 9964.67374.22659968.661372.38299978.721364.00979985.105362.3968 9988.78361.5554
 9998.84362.3378 10008.9363.459410018.96366.397810029.02369.797210039.08  374.83
10049.14379.753910057.16381.134110059.57381.999910071.47386.145510071.59386.1875
10083.38390.712210090.02 392.83210095.28394.373610103.18398.1038
#Mann= 3 , 0 , 0
9897.794  0.0671       09897.794  0.0671       010103.18  0.0671       0
#XS Ineff= 2 , 0
       0                               0
Bank Sta=9897.794,10103.18
Exp/Cntr=0.3,0.1

Type RM Length L Ch R = 1 ,10070.44,81.273600,81.273600,81.273600
XS GIS Cut Line= 6
823648.742400286790125.298922502823685.092391261790247.808982413
823685.583503212790266.460676308823677.929343898790318.030091855
 823678.40647975790355.587601002823685.724451878790415.128856522
#Sta/Elev= 30
9840.787409.32879850.802406.91199871.448403.32169881.805402.26069902.884 399.759
9913.424397.48259923.964 391.3239945.043379.83439950.089377.55949955.461374.9937
9965.766370.55169968.661368.83529975.854364.20949985.858 356.3799995.971352.2693
10006.12353.087610016.21 354.35110026.31354.456410036.41360.854810046.44367.3542
10056.44369.682610066.44372.578810077.03375.9821 10086.5379.594110096.57383.6563
10106.64388.8977 10116.7393.353910126.77395.258610136.89 391.24710137.02391.2633
#Mann= 3 , 0 , 0
9840.787  0.0868       09840.787  0.0868       010137.02  0.0868       0
#XS Ineff= 2 , 0
       0                               0
Bank Sta=9840.787,10137.02
Exp/Cntr=0.3,0.1

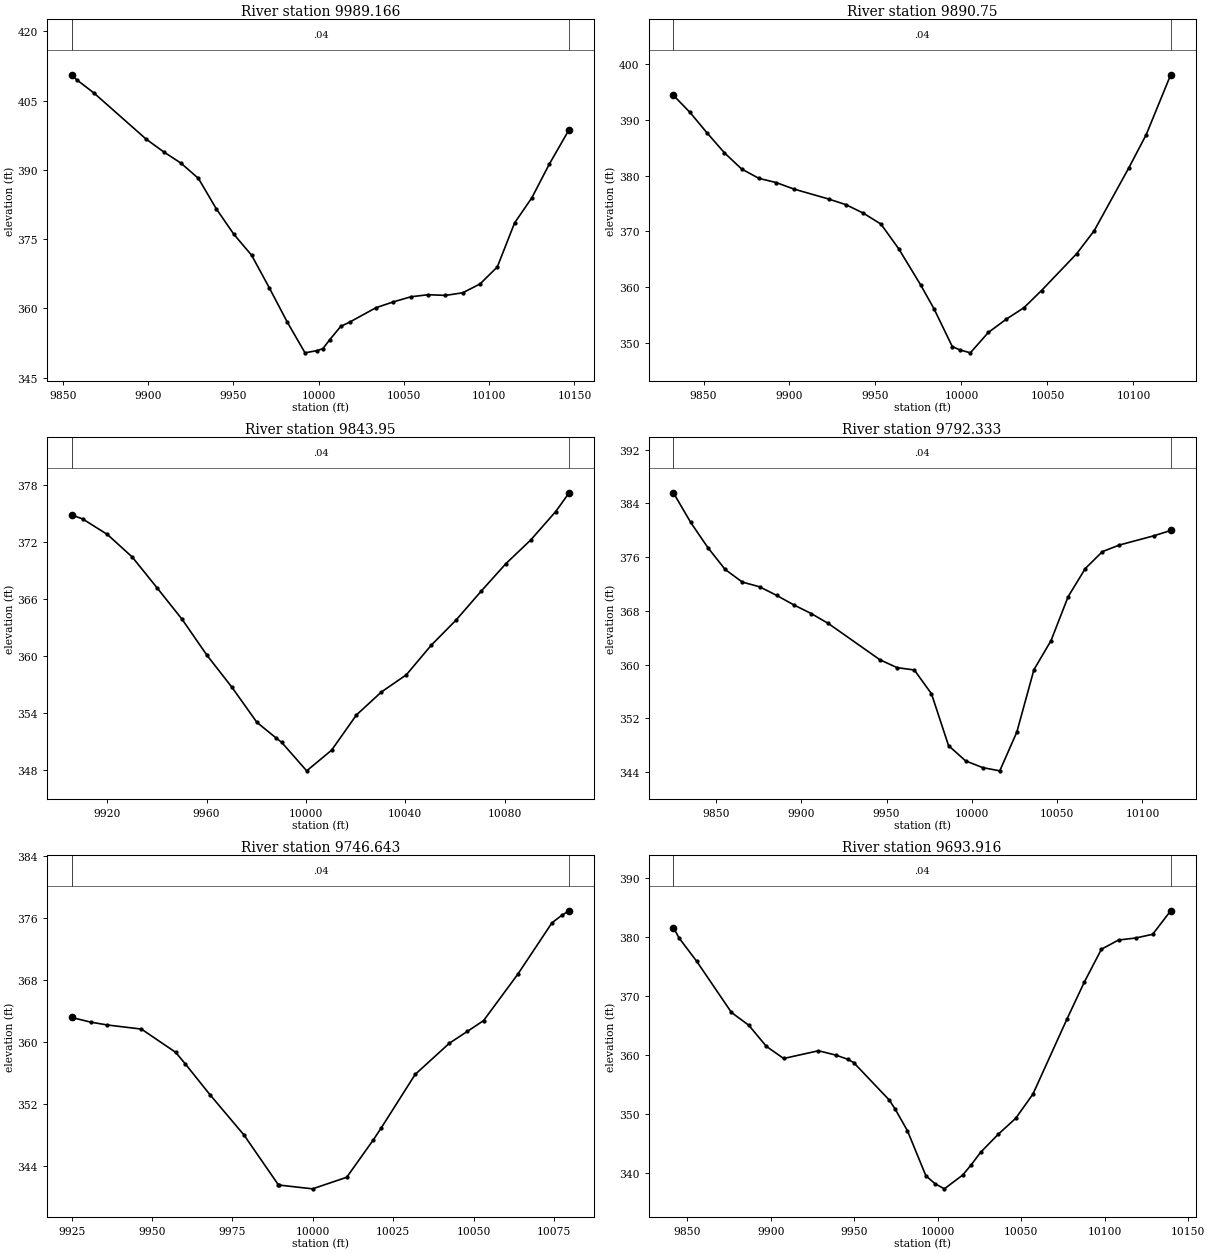
Type RM Length L Ch R = 1 ,9989.166,98.416600,98.416600,98.416600
XS GIS Cut Line= 6
823568.434389364 790142.26286189 823568.86136692790146.138758017
823584.171405345790219.166550027823608.513918028790300.009341055
 823616.69687809790335.353908523823631.415889565790426.599428401
#Sta/Elev= 30
9855.239410.56819857.992 409.5199868.192406.62479898.844396.62799909.061393.8906
9919.279391.42739929.496388.12759939.837381.61529950.266376.03129960.694371.4892
9971.123364.38389981.552357.04899991.981350.3761    9999350.855610002.44351.2769
10006.54 353.24810012.93356.092310018.19 357.03110033.57360.144110043.84361.4115
 10054.1362.512810064.24362.959310074.36362.809510084.49363.376410094.62365.2901
10104.75368.963510114.88378.496110125.01383.940510135.14391.158710146.89398.7145
#Mann= 3 , 0 , 0
9855.239    0.04       09855.239    0.04       010146.89    0.04       0
#XS Ineff= 2 , 0
       0                               0
Bank Sta=9855.239,10146.89
Exp/Cntr=0.3,0.1

Type RM Length L Ch R = 1 , 9890.75,46.799500,46.799500,46.799500
XS GIS Cut Line= 6
823485.457665253790155.337234465823487.938286611790206.207060087
823498.650296446790271.892820833823521.020946766790349.986909398
823531.414099633790401.947864088823535.756768877790439.131190931
#Sta/Elev= 27
9832.488394.32859842.162 391.2649852.174387.56769862.186384.04679872.197381.1562
9882.209379.49149892.327378.73389902.459377.58999922.723375.80459932.855374.7853
9942.987373.26719953.174371.3209 9963.48366.92629976.224360.48139984.138356.1322
9994.655349.4495    9999348.860510005.16348.3257 10015.6351.959310026.04354.3346
10036.36356.394310046.55359.457810066.95366.015710077.15370.123410097.37381.3944
10107.44387.305810121.67397.9911
#Mann= 3 , 0 , 0
9832.488    0.04       09832.488    0.04       010121.67    0.04       0
#XS Ineff= 2 , 0
       0                               0
Bank Sta=9832.488,10121.67
Exp/Cntr=0.3,0.1

Type RM Length L Ch R = 1 , 9843.95,51.617200,51.617200,51.617200
XS GIS Cut Line= 2
823458.767691553 790230.71329622823473.980979681790430.387702793
#Sta/Elev= 23
9905.754374.84499910.053374.44699920.082372.80499930.111370.4264 9940.14367.1734
9950.169363.88289960.198360.09569970.227356.74219980.256353.0598 9987.79351.4558
9990.285350.943110000.31347.957910010.34350.126810020.37353.8378 10030.4356.2468
10040.43358.050510050.46361.159510060.49363.813610070.52366.829210080.55 369.742
10090.58372.2393 10100.6375.217910106.01377.1897
#Mann= 3 , 0 , 0
9905.754    0.04       09905.754    0.04       010106.01    0.04       0
#XS Ineff= 2 , 0
       0                               0
Bank Sta=9905.754,10106.01
Exp/Cntr=0.3,0.1

Type RM Length L Ch R = 1 ,9792.333,45.690200,45.690200,45.690200
XS GIS Cut Line= 6
823434.181837542790154.906063311823415.357681475790302.534858735
823414.388342103 790327.65253398823414.549973842790329.645992077
823413.780455419790359.489071298823407.291022478790444.942726085
#Sta/Elev= 27
 9825.04 385.5779835.215381.15189845.296377.39279855.377374.15789865.458372.2761
9875.539371.5796 9885.62370.29019895.701368.87049905.782367.59779915.863366.1139
9946.106360.70699956.187359.53519966.268359.18739976.331355.63649986.338347.9193
9996.345 345.64710006.36344.646910016.36344.167410026.36 349.94310036.38359.2273
10046.41363.564710056.44370.109310066.47374.287410076.49376.809510086.52   377.8
10106.58379.165710116.55379.9611
#Mann= 3 , 0 , 0
 9825.04    0.04       0 9825.04    0.04       010116.55    0.04       0
#XS Ineff= 2 , 0
       0                               0
Bank Sta=9825.04,10116.55
Exp/Cntr=0.3,0.1

Type RM Length L Ch R = 1 ,9746.643,52.726500,52.726500,52.726500
XS GIS Cut Line= 2
 823397.02296254790244.656540453823344.200781614790390.006165758
#Sta/Elev= 23
9925.058363.15079925.424 363.0849930.981362.52379936.064362.16239946.703361.6303
9957.343358.63259960.259357.18349967.983353.18439978.623347.95229989.263 341.553
9989.536341.50989999.903341.025310010.54342.517710018.81347.342710021.18348.8247
10031.82355.783610042.46359.806910048.09361.3419 10053.1362.726110063.74368.7094
10074.38375.344410077.37376.288910079.71376.8907
#Mann= 3 , 0 , 0
9925.058    0.04       09925.058    0.04       010079.71    0.04       0
#XS Ineff= 2 , 0
       0                               0
Bank Sta=9925.058,10079.71
Exp/Cntr=0.3,0.1

Type RM Length L Ch R = 1 ,9693.916,98.416600,98.416600,98.416600
XS GIS Cut Line= 6
823374.665898001 790141.60994918823347.249323055790235.632876297
823334.477453124790269.771635511823316.133399988790309.509404287
823307.018318333790337.686862929823287.819553095790425.616458987
#Sta/Elev= 30
 9841.74381.54889845.271379.74419855.688375.84859876.521367.17419886.937365.0004
9897.354361.4488 9907.77359.38129928.603360.6918 9939.02359.95739946.098359.2568
 9949.68358.69429971.034352.33519974.637350.76489981.901347.13469992.943339.5098
9998.482338.164310003.99337.306910014.95339.6399 10019.9341.307610025.67 343.483
10036.18346.533810046.69349.243310057.01353.342110077.53366.137610087.79372.3184
10098.04377.8902 10108.3379.446210118.52379.786110128.71380.413210139.52384.3984
#Mann= 3 , 0 , 0
 9841.74    0.04       0 9841.74    0.04       010139.52    0.04       0
#XS Ineff= 2 , 0
       0                               0
Bank Sta=9841.74,10139.52
Exp/Cntr=0.3,0.1

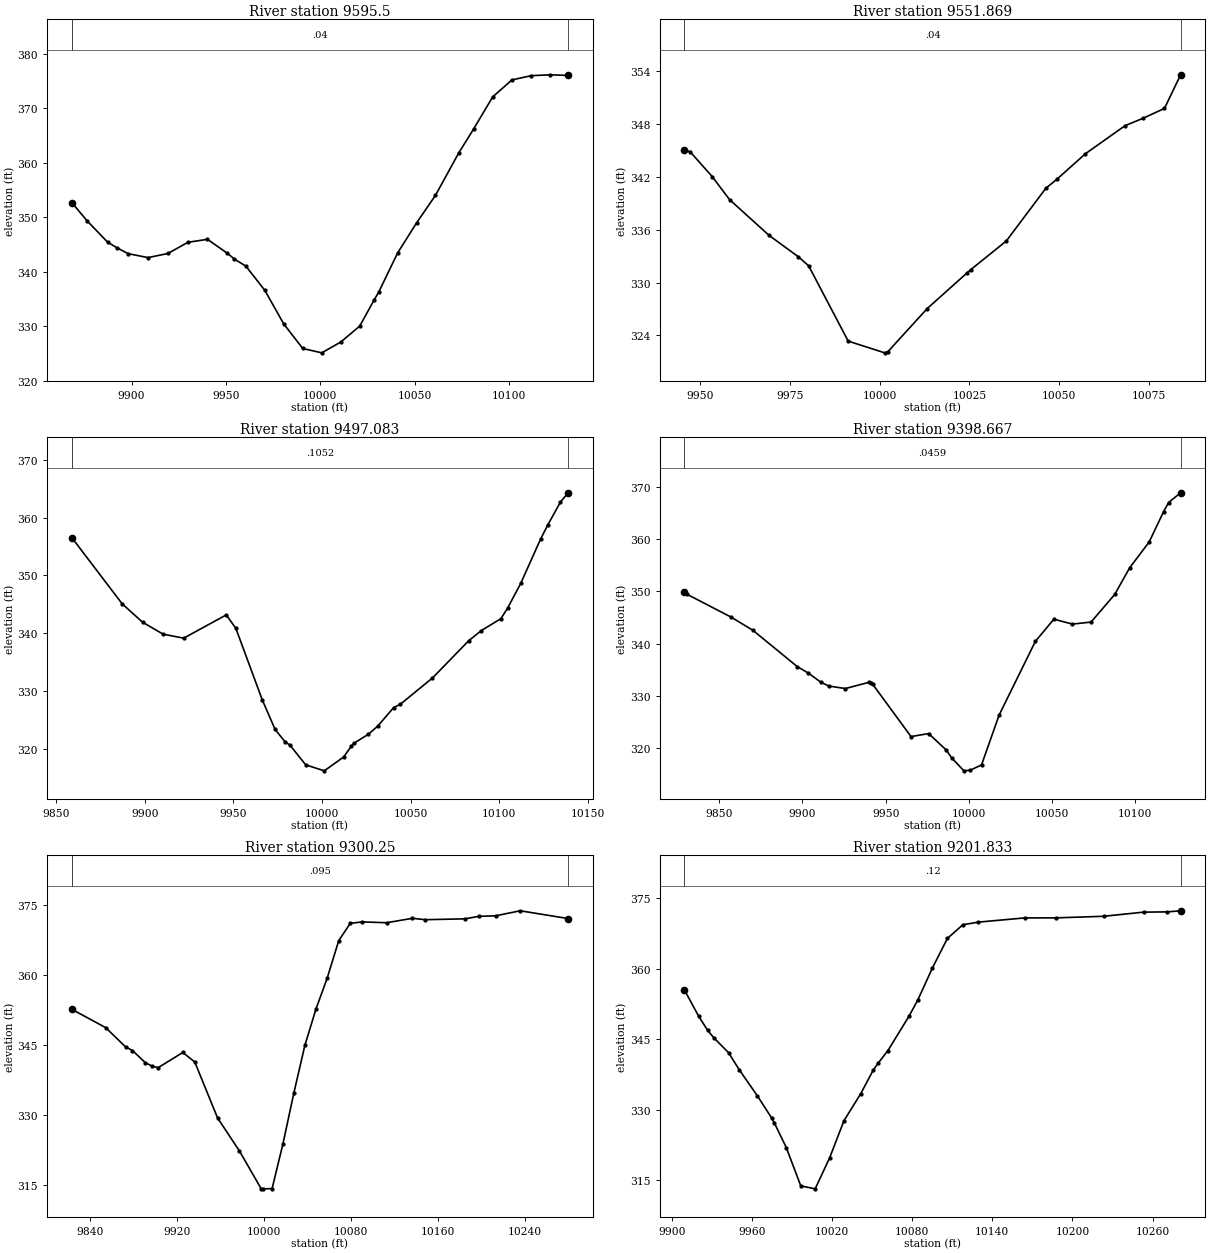
Type RM Length L Ch R = 1 ,  9595.5,43.630900,43.630900,43.630900
XS GIS Cut Line= 6
823254.672068892790157.560140523823227.068223768790238.931182939
 823225.40437773790255.736287359823231.085155039790312.436397651
823228.064685671 790357.35174776823216.961501938790414.154127186
#Sta/Elev= 30
9868.347352.68759876.473349.31469887.395345.39079892.395344.35049898.174343.3003
9908.734342.57329919.293343.32969929.853345.38259940.216345.93089950.462343.4427
9954.489342.30899960.588341.00049970.637336.54859980.676330.37649990.715325.8787
10000.78325.080910010.84327.064410020.89329.989710028.37334.696310030.94336.2271
10040.96343.413810050.98348.934310061.01353.999510073.39361.820910081.18366.1616
10091.37372.106510101.56 375.21310111.75375.986310121.94376.152510131.26376.0268
#Mann= 3 , 0 , 0
9868.347    0.04       09868.347    0.04       010131.26    0.04       0
#XS Ineff= 2 , 0
       0                               0
Bank Sta=9868.347,10131.26
Exp/Cntr=0.3,0.1

Type RM Length L Ch R = 1 ,9551.869,54.785800,54.785800,54.785800
XS GIS Cut Line= 2
823208.223852843790233.565787762823150.698607147790359.075414747
#Sta/Elev= 21
9945.672345.0223 9947.25344.86959953.409342.0438 9958.25 339.424 9969.25335.3602
 9977.41332.92669980.251331.90869991.251323.359310001.41322.027510002.25322.1372
10013.25  327.0610024.25331.075310025.41331.487910035.25 334.72710046.25340.7094
10049.41341.766610057.25344.628110068.25347.808110073.41348.680110079.25349.7737
10083.74 353.595
#Mann= 3 , 0 , 0
9945.672    0.04       09945.672    0.04       010083.74    0.04       0
#XS Ineff= 2 , 0
       0                               0
Bank Sta=9945.672,10083.74
Exp/Cntr=0.3,0.1

Type RM Length L Ch R = 1 ,9497.083,98.416600,98.416600,98.416600
XS GIS Cut Line= 6
823233.090272323790140.377181472823175.630146381790229.961858098
823162.991067821790240.221507621823131.244100498790253.747430664
823115.658438315790271.804370603823069.956254641790358.884892866
#Sta/Elev= 30
9858.874356.55519887.302345.08139898.848341.88829910.393339.82939922.012339.1385
9946.021343.16939951.434340.82989966.372328.41349973.554 323.3359979.252321.1596
9981.839320.64239990.842317.195210001.32316.156810012.23318.553710016.59320.4363
10018.24  320.9810026.14322.479610031.45323.897410040.44 327.112 10044.1327.6599
10062.33332.236810082.86338.713910089.85340.438510101.01342.530610104.89344.4384
10112.17348.648810123.32356.293110127.44358.773810134.48362.675310138.82364.3193
#Mann= 3 , 0 , 0
9858.874  0.1052       09858.874  0.1052       010138.82  0.1052       0
#XS Ineff= 2 , 0
       0                               0
Bank Sta=9858.874,10138.82
Exp/Cntr=0.3,0.1

Type RM Length L Ch R = 1 ,9398.667,98.416700,98.416700,98.416700
XS GIS Cut Line= 6
823166.165737432790087.093316114823109.910527032790135.976436448
 823085.66392783790162.816585369823072.915147512790185.241081049
823052.452059055790243.911340037823004.535884967 790331.12246708
#Sta/Elev= 30
9829.035349.90479830.579 349.4579857.075345.07999870.323342.52219896.819335.6005
9903.562334.33969910.887332.62989915.722331.86629925.805331.38129939.732332.5508
9941.075 332.4349942.244332.1906 9965.25322.1715 9975.86322.74979986.448319.5911
9989.608318.11949997.037315.6068   10001 315.74910007.62316.736310018.22326.3098
10039.99340.424510051.11344.674410062.22343.732910073.45344.117710087.68349.4165
10096.71354.550710108.34359.450210117.07365.297610120.03367.023210127.27368.9011
#Mann= 3 , 0 , 0
9829.035  0.0459       09829.035  0.0459       010127.27  0.0459       0
#XS Ineff= 2 , 0
       0                               0
Bank Sta=9829.035,10127.27
Exp/Cntr=0.3,0.1

Type RM Length L Ch R = 1 , 9300.25,98.416700,98.416700,98.416700
XS GIS Cut Line= 6
823159.998887769790082.183403962823061.954170089790144.438265252
822972.094832891790149.916971059822923.219525481 790163.74471398
822853.420238892 790204.35550486 822761.37282413790277.505382491
#Sta/Elev= 30
9823.192352.61739854.401348.67479872.667344.54769879.014343.77019890.836341.1629
9897.413 340.3779902.658  340.099925.343343.34499936.361341.30749957.319329.3068
9977.463322.21159997.501 314.091    9999314.084910007.51314.132410017.52323.7679
10027.53334.640110037.68344.881810047.89352.673910058.16 359.26410068.82367.3491
10079.48371.0651 10090.6371.363110113.03371.189210136.62372.139710148.49371.8411
10185.31372.026910197.83372.566310213.09 372.66810235.81373.753910279.84372.0885
#Mann= 3 , 0 , 0
9823.192   0.095       09823.192   0.095       010279.84   0.095       0
#XS Ineff= 2 , 0
       0                               0
Bank Sta=9823.192,10279.84
Exp/Cntr=0.3,0.1

Type RM Length L Ch R = 1 ,9201.833,98.416600,98.416600,98.416600
XS GIS Cut Line= 6
823094.562319055790017.077807345823067.100673197790031.080714089
822973.279905661790069.268168702822916.330409458790096.918422782
822838.878027842790141.899440142822767.237259292790190.550901054
#Sta/Elev= 30
  9909.4355.53549920.134349.8974 9926.84346.89989931.359 345.3459942.497342.1446
9950.531338.48949964.123332.93179974.935328.16249976.822327.16219985.748 321.922
9996.561313.781310007.34313.143410018.12319.702110028.89327.641410041.52333.4319
10050.73338.377110054.65339.962310061.84342.597310077.54349.878210084.08353.2892
10095.19360.213710106.37366.479710117.93369.3866 10129.5369.948910164.19 370.843
10187.32370.853710223.26371.191510253.31 372.07510271.11372.127810280.99372.3648
#Mann= 3 , 0 , 0
  9909.4    0.12       0  9909.4    0.12       010280.99    0.12       0
#XS Ineff= 2 , 0
       0                               0
Bank Sta=9909.4,10280.99
Exp/Cntr=0.3,0.1

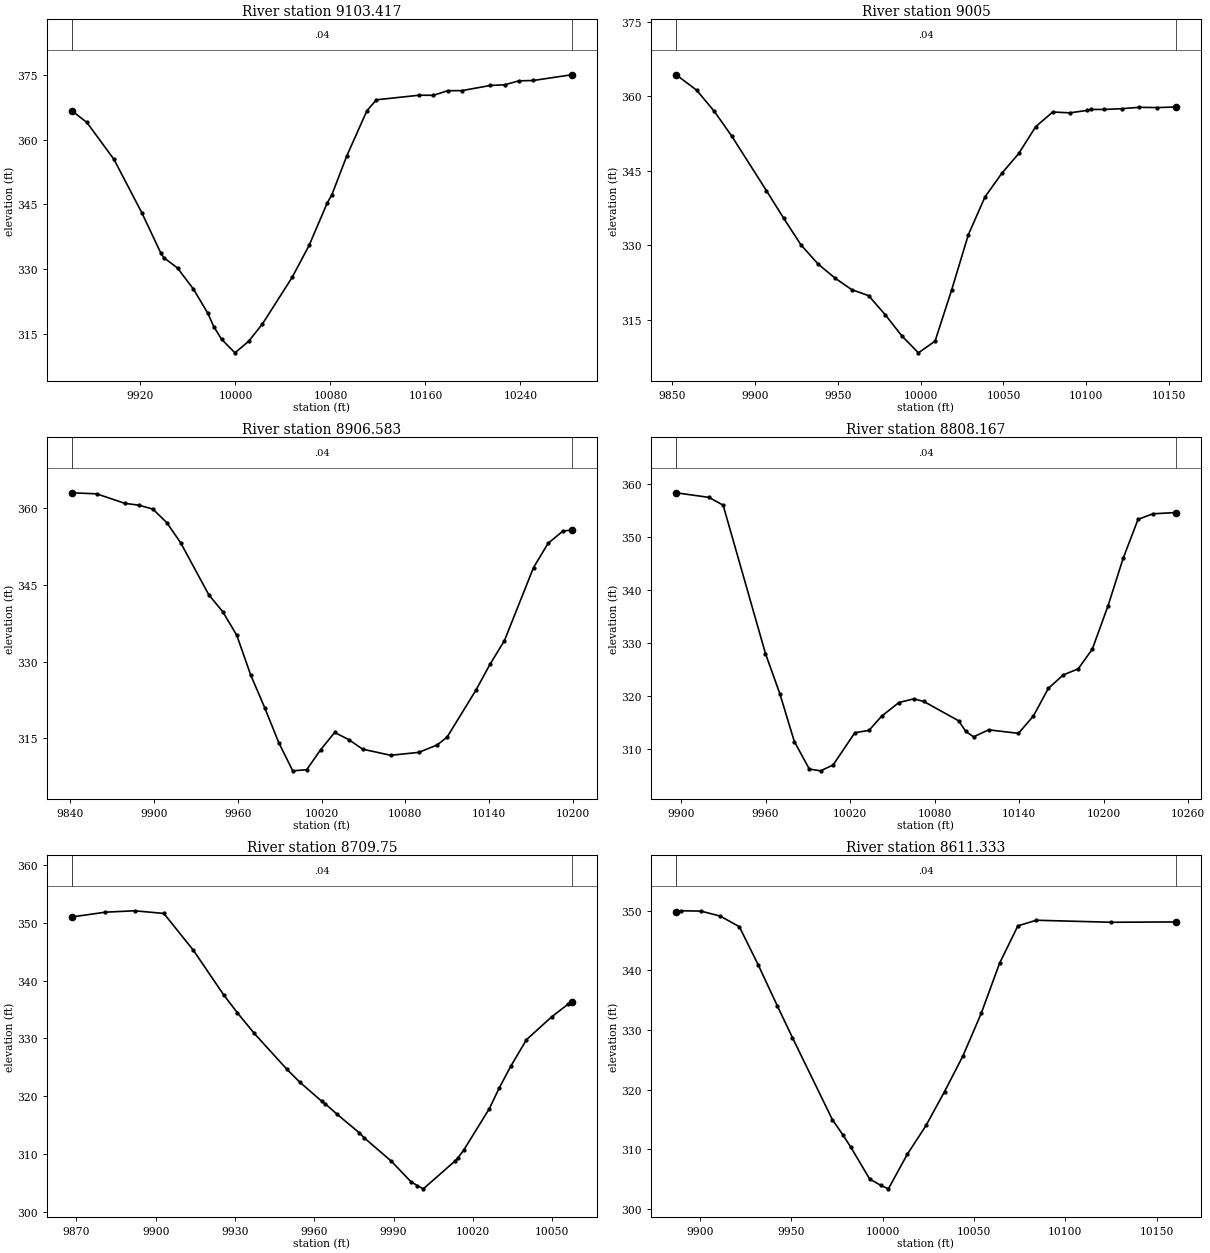
Type RM Length L Ch R = 1 ,9103.417,98.416700,98.416700,98.416700
XS GIS Cut Line= 6
823036.184643312789905.504840341 822970.97846728789946.570783726
822944.481897032789979.143758385822922.011922274790020.200777332
822893.074791421790051.335970229822717.944384574 790170.53512194
#Sta/Elev= 30
9862.395366.67199874.993363.96439897.721355.43989921.373342.96859937.221333.7061
9939.711332.64939951.269330.25819964.659325.37299976.792319.7685 9981.82316.6726
9988.402313.73499999.631310.602710011.11313.262310022.64317.243810047.79328.0891
10062.05335.477310077.35345.3347 10081.3347.264710093.78356.217610110.77366.6962
10118.74369.219510154.74370.279310166.73370.262610178.73371.325810190.72 371.345
 10214.7372.5422 10226.7 372.68910238.69373.608710250.68373.690510283.13375.0157
#Mann= 3 , 0 , 0
9862.395    0.04       09862.395    0.04       010283.13    0.04       0
#XS Ineff= 2 , 0
       0                               0
Bank Sta=9862.395,10283.13
Exp/Cntr=0.3,0.1

Type RM Length L Ch R = 1 ,    9005,98.416700,98.416700,98.416700
XS GIS Cut Line= 6
823026.699221651789884.953093425822949.333181682 789909.82738139
822912.375578762789916.488223544822844.293792211789920.615524982
822777.273233091789936.513442563822734.407624065789951.668917386
#Sta/Elev= 30
9852.499364.36459864.866361.26769875.438357.04169886.009352.03329906.987341.0136
9917.426335.43599927.865330.07119938.184326.21259948.345323.40019958.506321.0501
9968.667319.84429978.718315.9875 9988.73 311.7259998.742308.319710008.76310.6812
 10018.8321.023910028.85332.136910038.91339.7605 10049.1 344.53210059.29348.5101
10069.49 353.90810079.77356.857910090.15356.692910100.53357.184510102.91357.3759
10110.95357.377410121.51357.530410132.07357.809810142.63357.751910154.03357.8673
#Mann= 3 , 0 , 0
9852.499    0.04       09852.499    0.04       010154.03    0.04       0
#XS Ineff= 2 , 0
       0                               0
Bank Sta=9852.499,10154.03
Exp/Cntr=0.3,0.1

Type RM Length L Ch R = 1 ,8906.583,98.416600,98.416600,98.416600
XS GIS Cut Line= 6
823052.441582894789817.485374686822974.274532808789824.325045492
822893.427868641789819.968993214822822.457348327789821.686790006
822750.884035346 789834.50690434 822698.98679401789850.047777364
#Sta/Elev= 30
9841.447363.01479859.105362.80699879.269360.95189889.278360.58729899.288359.8335
9909.297357.18059919.307353.20489939.339343.08519949.355339.76429959.372335.1635
9969.388327.35829979.405320.97469989.421 314.1719999.427308.669810009.43308.8974
10019.43312.818910029.43316.169110039.43314.784710049.45312.903610069.47311.7092
10089.63312.2802 10102.8313.7348 10109.9315.278910130.35324.375810140.58329.4992
 10150.9334.1324 10171.7348.395610182.09353.127110192.61355.507310198.98355.7587
#Mann= 3 , 0 , 0
9841.447    0.04       09841.447    0.04       010198.98    0.04       0
#XS Ineff= 2 , 0
       0                10027.42       0
Bank Sta=9841.447,10198.98
Exp/Cntr=0.3,0.1

Type RM Length L Ch R = 1 ,8808.167,98.416700,98.416700,98.416700
XS GIS Cut Line= 6
823018.279538204789739.039198015  822954.2398453789740.049594456
822930.258198555789734.694633271822903.160213126 789722.11628948
822884.034137532789722.350997178822679.731933103789794.806245381
#Sta/Elev= 30
9896.487358.40379919.846357.53129929.865356.05739959.903328.00879970.132320.3879
9980.378311.36669991.044 306.156    9999305.818310007.91306.923810023.35313.0259
10033.42313.474510042.31316.146310054.58 318.73110065.19319.434210072.23318.9468
10097.02315.280510102.15313.258410107.64312.249810118.25313.571910139.47312.9127
10150.08316.181510160.69321.4211 10171.3323.958510181.91325.1104 10191.9  328.84
10203.13337.084510213.74345.980910224.35353.372210234.96354.433710251.16354.6589
#Mann= 3 , 0 , 0
9896.487    0.04       09896.487    0.04       010251.16    0.04       0
#XS Ineff= 2 , 0
       0                10028.13       0
Bank Sta=9896.487,10251.16
Exp/Cntr=0.3,0.1

Type RM Length L Ch R = 1 , 8709.75,98.416700,98.416700,98.416700
XS GIS Cut Line= 6
822956.522465074789597.226659763822918.432970524789615.000596864
822880.981199658789638.250205994822870.793031812789648.023156579
822832.166255672 789701.12422765822813.916632881789715.192540249
#Sta/Elev= 30
9868.298350.96889880.971 351.7939892.024352.03269903.076351.57279914.263345.2109
 9925.71337.53619930.884 334.4519937.323330.86719949.559324.73299954.477322.4885
9962.765319.20129964.227318.70879968.594316.95019977.053313.73439978.839312.8921
9989.178308.83429996.524305.3267    9999304.612610001.28 304.06310013.37308.8959
10014.34309.379410016.56310.729410026.26317.891810029.99 321.44110034.34 325.176
10040.32329.789610049.81333.713310056.16335.952810057.07336.199510057.43336.2166
#Mann= 3 , 0 , 0
9868.298    0.04       09868.298    0.04       010057.43    0.04       0
#XS Ineff= 2 , 0
       0                               0
Bank Sta=9868.298,10057.43
Exp/Cntr=0.3,0.1

Type RM Length L Ch R = 1 ,8611.333,98.416600,98.416600,98.416600
XS GIS Cut Line= 6
822947.660389241789576.876707856  822883.0507774789595.702412769
822863.667870916789595.865150047822812.741894421789584.108558338
822767.117719442789582.493064376822681.524670834789604.407553861
#Sta/Elev= 24
9887.027349.72889889.873349.96049900.571349.90939911.155349.07199921.631347.2921
9932.107340.81279942.331334.0984 9950.67328.73829972.539314.99489978.198312.4883
9982.718310.34899992.924 305.062    9999303.998710003.19303.409610013.51309.1662
10023.82314.028110033.94 319.69310043.99325.650410054.03332.809110064.04341.1672
10074.06347.432910084.17348.377110125.24348.0366 10160.5348.0951
#Mann= 3 , 0 , 0
9887.027    0.04       09887.027    0.04       0 10160.5    0.04       0
#XS Ineff= 2 , 0
       0                               0
Bank Sta=9887.027,10160.5
Exp/Cntr=0.3,0.1

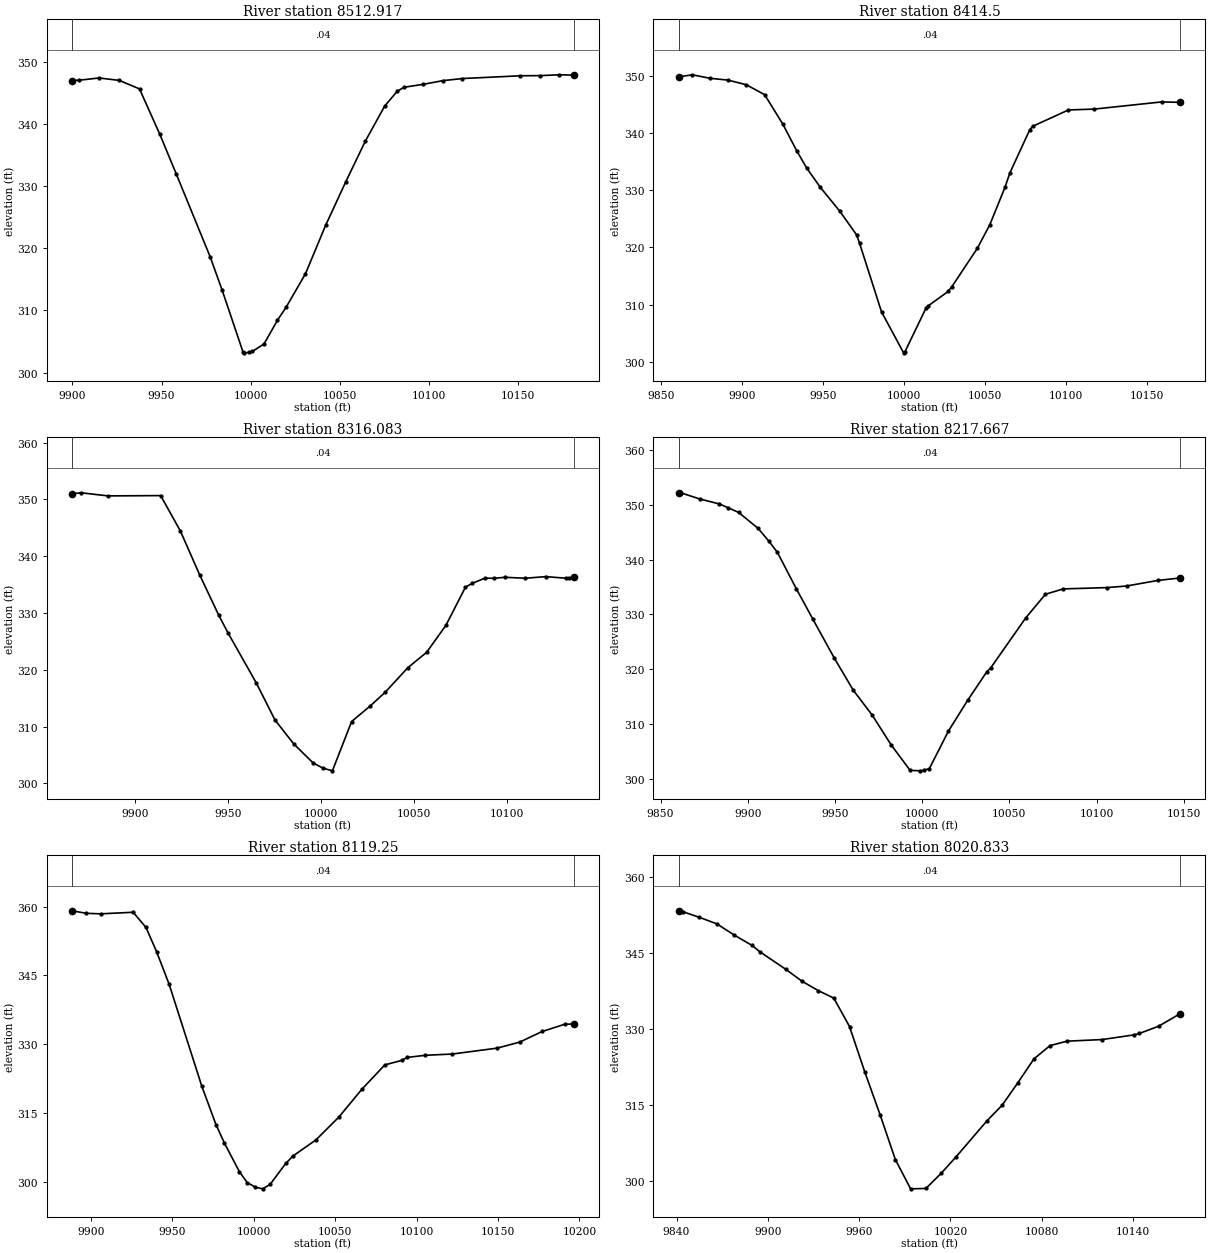
Type RM Length L Ch R = 1 ,8512.917,98.416700,98.416700,98.416700
XS GIS Cut Line= 6
822908.619411324789447.768498282822895.664690441789453.984440104
822856.295056568 789475.31865203822804.588146366789507.606605152
822773.704957668789524.128373857822657.481761089789574.222294906
#Sta/Elev= 30
9899.793347.03379903.807347.08179914.918347.44329926.291347.05129937.665345.6783
9949.039338.38149958.271331.99169977.373318.59439983.965313.33559995.716 303.336
9996.412303.1703    9999303.2328   10001303.394710007.57 304.60910015.04308.3926
 10019.9310.492410030.78315.885210042.12323.695210053.46330.729610064.41337.2641
 10075.3342.918710082.39345.314810086.19345.949410097.07346.424610107.96347.0122
10118.85347.350210151.52 347.79710162.41347.8195 10173.3347.956710181.49347.8995
#Mann= 3 , 0 , 0
9899.793    0.04       09899.793    0.04       010181.49    0.04       0
#XS Ineff= 2 , 0
       0                               0
Bank Sta=9899.793,10181.49
Exp/Cntr=0.3,0.1

Type RM Length L Ch R = 1 ,  8414.5,98.416700,98.416700,98.416700
XS GIS Cut Line= 6
822872.549831668789352.166602695822802.062701455789387.820500926
822775.787123673789405.421010974822727.146207307789450.745039651
822686.623854589789480.023964618 822614.82566102789520.668651012
#Sta/Elev= 30
9860.712349.75869869.105350.13839880.222349.52279891.339349.20389902.533 348.398
9913.821346.66789925.109341.50529933.632336.87039939.713333.88949948.214330.4874
 9960.25326.30879970.582322.19359972.407320.73789985.986308.73419999.593301.5988
10000.22301.673810013.35309.3697 10014.8309.809110027.06312.311410029.43313.1741
10045.09319.846310052.81323.980710062.17330.508510065.15332.993810077.49340.5742
10079.24341.145610101.31343.996710117.29344.150610158.75345.398810170.34 345.326
#Mann= 3 , 0 , 0
9860.712    0.04       09860.712    0.04       010170.34    0.04       0
#XS Ineff= 2 , 0
       0                               0
Bank Sta=9860.712,10170.34
Exp/Cntr=0.3,0.1

Type RM Length L Ch R = 1 ,8316.083,98.416600,98.416600,98.416600
XS GIS Cut Line= 6
822859.444093948 789317.43003573822780.089457789789343.949315194
822758.814217814789345.398662039822697.021755998789334.447783625
 822671.93176845789338.530295259822601.304834309789366.263850322
#Sta/Elev= 30
9866.174 350.9879871.003351.1701 9885.51350.62079913.791350.67459924.378344.4434
9934.738336.72549944.991329.61839950.026 326.468 9965.15317.70629975.197311.1799
9985.282306.95749995.648 303.622   10001302.679610006.09302.205310016.43310.8918
10026.44313.631310034.43 316.03210046.61320.359210056.74323.075810067.13327.8425
10077.62334.554610081.18335.217410088.11336.1406 10092.9336.107210098.85336.2884
10109.78336.119810120.72336.406110131.65336.123710133.25336.133310135.87336.3752
#Mann= 3 , 0 , 0
9866.174    0.04       09866.174    0.04       010135.87    0.04       0
#XS Ineff= 2 , 0
       0                               0
Bank Sta=9866.174,10135.87
Exp/Cntr=0.3,0.1

Type RM Length L Ch R = 1 ,8217.667,98.416700,98.416700,98.416700
XS GIS Cut Line= 6
822816.179903404 789202.75892876822765.204225821789226.949923086
  822689.5799908 789259.25484398822652.906964962789275.943461353
 822613.98313351789296.016235227822560.104763522789332.249838402
#Sta/Elev= 30
 9860.34352.16569861.646 352.1579872.715351.01849883.784350.12869888.892349.4224
9894.853348.57169905.922345.68379912.217343.30779916.987341.32579927.861334.6716
9937.257329.17879949.609322.04689960.484316.18679971.358311.63749982.232306.2026
9993.106 301.557    9999301.4657   10001301.568410004.15301.876610015.11308.7316
10026.06314.2999   10037319.492110039.31320.229210059.46329.376810070.71333.6611
10080.89334.638510105.95334.876210117.21335.165710135.18 336.18710148.04336.6362
#Mann= 3 , 0 , 0
 9860.34    0.04       0 9860.34    0.04       010148.04    0.04       0
#XS Ineff= 2 , 0
       0                               0
Bank Sta=9860.34,10148.04
Exp/Cntr=0.3,0.1

Type RM Length L Ch R = 1 , 8119.25,98.416600,98.416600,98.416600
XS GIS Cut Line= 6
 822747.65032426    789088.92688822711.315500029789124.013945473
822669.546361292789167.217420506822668.124419293789168.623863165
822612.466390675789224.636849201822532.056880004789309.094027596
#Sta/Elev= 30
9888.396359.08529897.139358.53019905.982358.4196 9925.93358.76139933.785355.4575
9940.278350.19349947.993343.08799968.097 320.8289976.767312.49529982.006308.4204
9991.154302.22369995.916 299.857   10001298.840510005.43298.480610009.99299.4311
10019.62304.007610024.09305.643510038.18309.148810052.28314.133710066.38320.1822
10080.47325.488410090.79326.473110094.27327.126110105.29327.587610121.89327.8606
 10149.5329.150310163.31330.463310177.12332.773810190.92334.349110196.58334.4073
#Mann= 3 , 0 , 0
9888.396    0.04       09888.396    0.04       010196.58    0.04       0
#XS Ineff= 2 , 0
       0                               0
Bank Sta=9888.396,10196.58
Exp/Cntr=0.3,0.1

Type RM Length L Ch R = 1 ,8020.833,98.416700,98.416700,98.416700
XS GIS Cut Line= 6
822626.920312123788993.613712488822586.694970093789069.923266461
822579.995901847789096.055119423822575.039223054789178.885412868
822562.768957824789227.133882661822515.800981456789295.673460194
#Sta/Elev= 30
9841.316353.29759844.527353.07219854.946352.01269866.523 350.7119878.101348.4751
9889.678346.44769894.801345.2019 9911.67 341.7719922.501339.38649933.074337.5502
9943.398336.05839953.721330.44459963.788321.45199973.824313.0206 9983.86304.1748
9993.896298.398810003.94298.472110013.94301.454110023.94304.776210044.02 311.807
10054.14314.936610064.43319.365110074.99324.066310085.55326.675810096.73327.5547
 10119.7327.8699 10140.8328.795710144.31329.0764   10157330.5172 10171.2332.9997
#Mann= 3 , 0 , 0
9841.316    0.04       09841.316    0.04       0 10171.2    0.04       0
#XS Ineff= 2 , 0
       0                               0
Bank Sta=9841.316,10171.2
Exp/Cntr=0.3,0.1