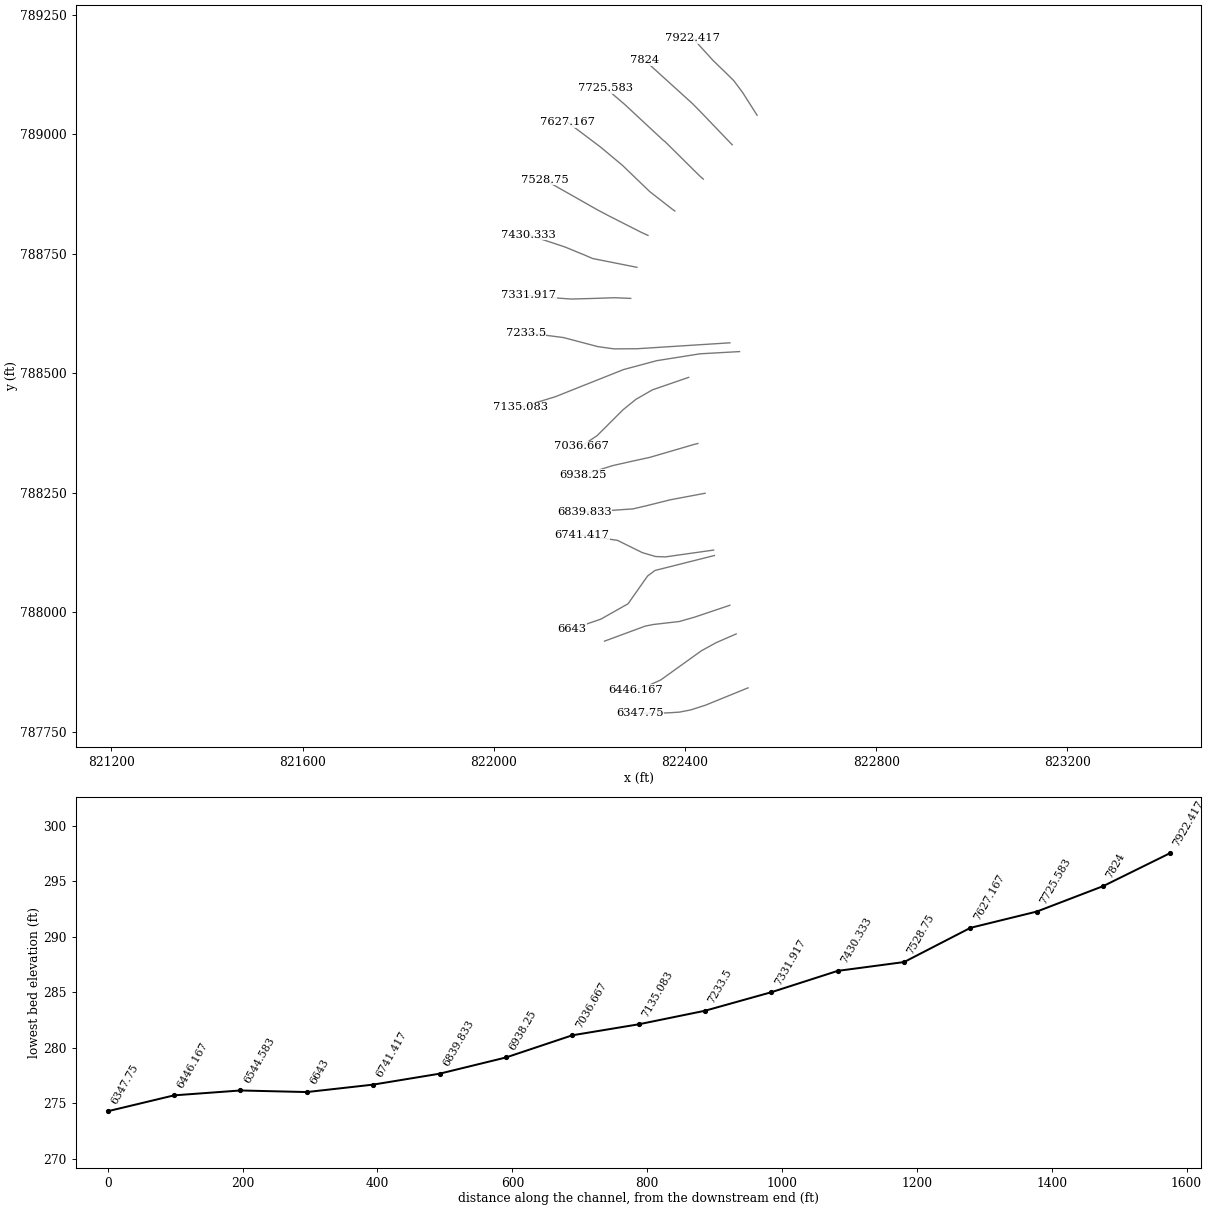
HEC-RAS study 17397_ras.prj: 17397

--- 17397_ras.g01 (geometry) --- (continued)

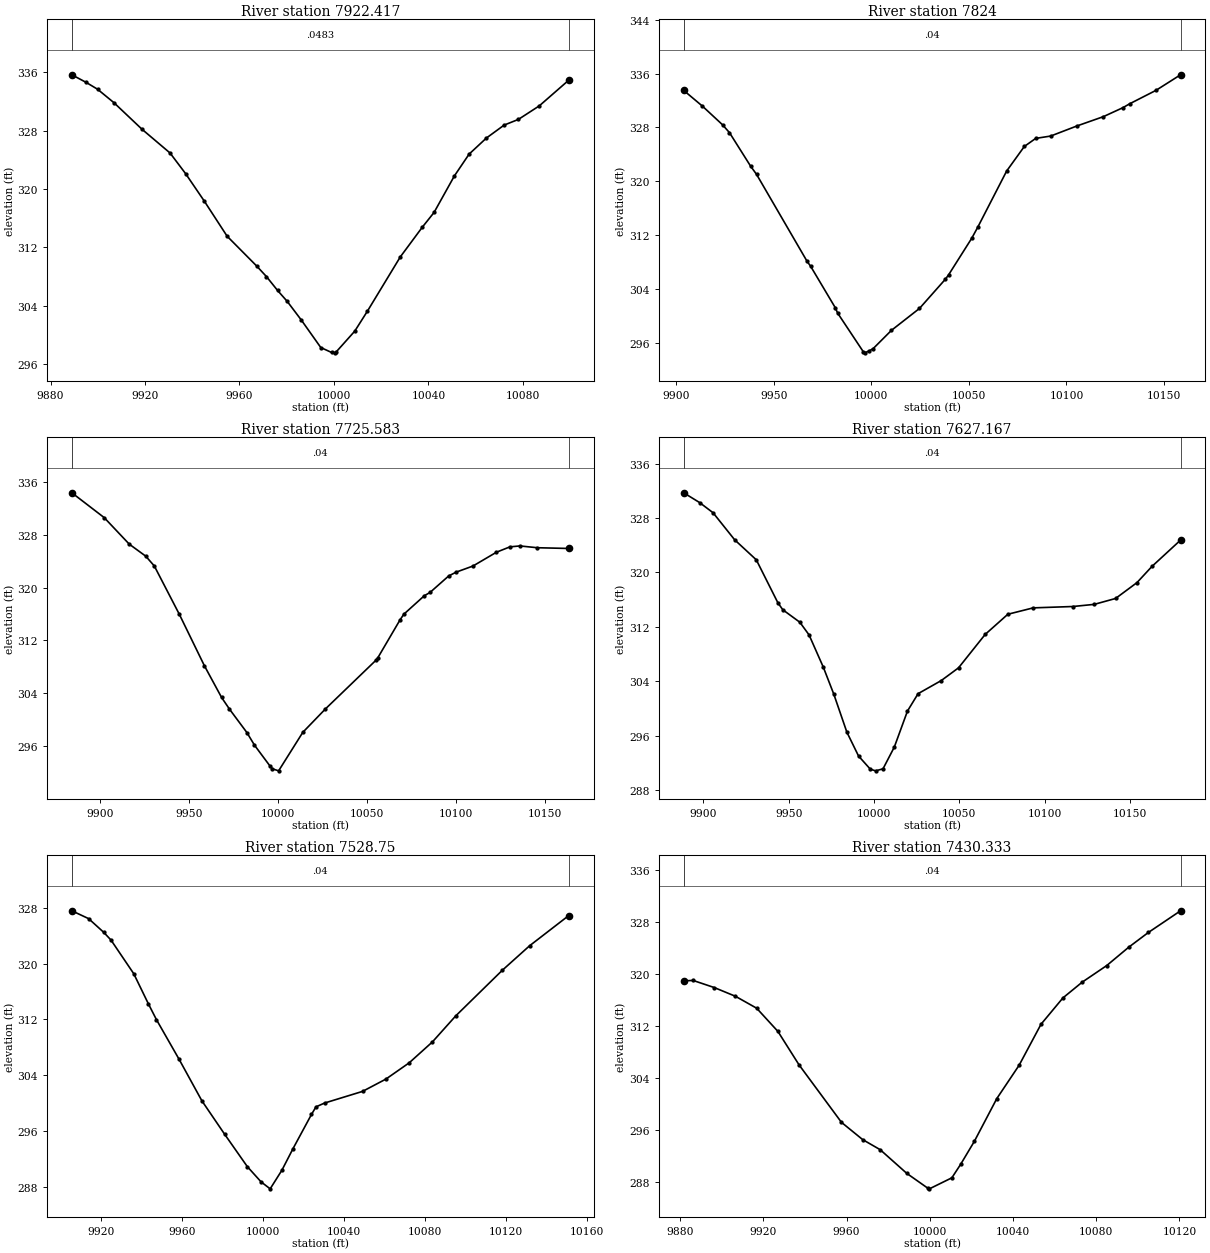
Type RM Length L Ch R = 1 ,7922.417,98.416700,98.416700,98.416700
XS GIS Cut Line= 6
822550.843184996789039.918427169822520.741371403789087.249433426
822502.180182471789112.128011098 822485.93946081789128.217442562
822459.022846996789154.204033218822416.583259149789200.774200828
#Sta/Elev= 30
9889.007335.64949895.029334.61299899.895333.6698 9906.88331.81059918.731 328.178
9930.582324.92869937.164322.10399945.099318.32789954.769313.51289967.246309.4389
9971.423307.97789976.139306.0725 9980.22304.57529986.246301.99049994.428298.2489
    9999297.571510000.26297.5213   10001297.664310008.82300.499610014.16303.2304
10028.09310.672310037.49314.782210042.39316.771410051.02321.791110057.23324.7689
10064.55326.974110072.08328.752110078.08329.525910086.93331.381410099.42334.9084
#Mann= 3 , 0 , 0
9889.007  0.0483       09889.007  0.0483       010099.42  0.0483       0
#XS Ineff= 2 , 0
       0                               0
Bank Sta=9889.007,10099.42
Exp/Cntr=0.3,0.1

Type RM Length L Ch R = 1 ,    7824,98.416600,98.416600,98.416600
XS GIS Cut Line= 5
822498.795625048788978.061904003822432.891752933789046.729019303
822431.543652145 789048.20639003822415.432102085789064.440819964
822315.654350041789154.858044755
#Sta/Elev= 30
9903.824333.4964 9913.44331.16099923.747328.39549927.301327.22989938.189322.2359
9941.161321.05389967.072 308.1499968.882307.42099981.514301.27559982.743 300.468
9995.955294.70689996.603294.5706    9999294.8679   10001295.209710010.29297.8985
 10024.7 301.15710037.95305.4848 10039.6306.129810051.45311.550710054.49313.1619
10069.38321.537410078.44325.178410084.27326.375510091.93326.722610105.43328.2232
10118.92329.596710128.95330.928210132.42331.506410145.91333.498710158.52335.8105
#Mann= 3 , 0 , 0
9903.824    0.04       09903.824    0.04       010158.52    0.04       0
#XS Ineff= 2 , 0
       0                               0
Bank Sta=9903.824,10158.52
Exp/Cntr=0.3,0.1

Type RM Length L Ch R = 1 ,7725.583,98.416700,98.416700,98.416700
XS GIS Cut Line= 6
822438.308748806788906.175578011 822430.48204967788913.153297345
822358.865205247788984.081092648822354.603734664788987.375439224
822273.774694292789062.597764675822234.124818507789096.466558696
#Sta/Elev= 30
9884.321 334.3529902.523330.59029916.597326.57849925.853324.76179930.671323.2783
9944.745315.9564 9958.82308.17939968.486 303.3779972.894301.62119982.697298.0713
9986.968296.16139995.602293.03349997.016292.584110000.53 292.27710014.12298.1018
10026.87301.6554 10055.1  308.9810056.23309.364210068.76315.120210070.91315.9828
10082.42318.776910085.59 319.26410096.08321.761610100.26322.340310109.74323.2681
10122.96325.359910130.51326.169510136.11326.307610145.91326.036610163.56 325.925
#Mann= 3 , 0 , 0
9884.321    0.04       09884.321    0.04       010163.56    0.04       0
#XS Ineff= 2 , 0
       0                               0
Bank Sta=9884.321,10163.56
Exp/Cntr=0.3,0.1

Type RM Length L Ch R = 1 ,7627.167,98.416700,98.416700,98.416700
XS GIS Cut Line= 6
822378.824594473788839.559737257822374.245325219788842.665331286
822326.495511049788879.844715578822268.822253394788935.325232047
822223.588266692788973.026018357822154.571319123789025.053417408
#Sta/Elev= 30
9888.391 331.7329897.724 330.2959905.642328.79079918.315324.80779930.989321.8651
9943.663315.53369946.556314.50979956.505312.68299961.924310.81719970.303306.0577
9976.437302.09349984.101296.5016 9990.95292.9901  9997.9291.0411   10001290.8103
 10005.3 291.10910011.92 294.30610019.65299.616410025.86302.165610039.45304.0959
10049.58305.9694 10065.2310.8849 10078.5313.854310093.36314.794310116.64314.9945
10129.16315.308910141.68316.1782 10154.2318.506110163.09320.912710179.79324.7684
#Mann= 3 , 0 , 0
9888.391    0.04       09888.391    0.04       010179.79    0.04       0
#XS Ineff= 2 , 0
       0                               0
Bank Sta=9888.391,10179.79
Exp/Cntr=0.3,0.1

Type RM Length L Ch R = 1 , 7528.75,98.416600,98.416600,98.416600
XS GIS Cut Line= 6
822322.550784396788788.440779996822309.340044645788794.429189008
822238.917771642 788830.17325511822237.184911712788831.171852358
 822216.93462094788841.812245866822106.450719683788904.539680686
#Sta/Elev= 26
9905.521 327.5589913.811 326.4349921.287324.46819924.893323.35319936.107318.5415
9943.381314.19619947.322311.95679958.536306.2616 9969.75300.33499980.965295.5554
9992.179290.9116    9999288.717610003.47287.724210009.23290.372710014.76293.4865
10023.88298.3868 10026.1299.470310030.33300.0138 10049.1301.6849 10060.6303.4418
 10072.1305.7696 10083.6308.7713 10095.1312.496210118.09319.0283 10131.6 322.547
10150.92326.8721
#Mann= 3 , 0 , 0
9905.521    0.04       09905.521    0.04       010150.92    0.04       0
#XS Ineff= 2 , 0
       0                               0
Bank Sta=9905.521,10150.92
Exp/Cntr=0.3,0.1

Type RM Length L Ch R = 1 ,7430.333,98.416700,98.416700,98.416700
XS GIS Cut Line= 6
822299.423587584788721.645212418822206.758486458788740.034111374
822185.791625721788749.084409693 822183.90677023788749.753229385
822148.238956654788764.398829238822071.311683167788789.875456268
#Sta/Elev= 25
9881.691318.90519886.201318.97669896.396317.88229906.591316.53829916.786 314.705
9926.981311.14539937.176305.98779957.566 297.1529967.761294.49949976.163292.9517
 9988.97289.3059    9999287.0448 9999.84 286.92910010.63288.624910014.81290.6722
10021.44 294.22910032.25300.814210042.97305.9337 10053.5312.239910064.04 316.291
10073.28318.706910085.11321.267710095.64324.077410105.09326.346610120.59329.6862
#Mann= 3 , 0 , 0
9881.691    0.04       09881.691    0.04       010120.59    0.04       0
#XS Ineff= 2 , 0
       0                               0
Bank Sta=9881.691,10120.59
Exp/Cntr=0.3,0.1

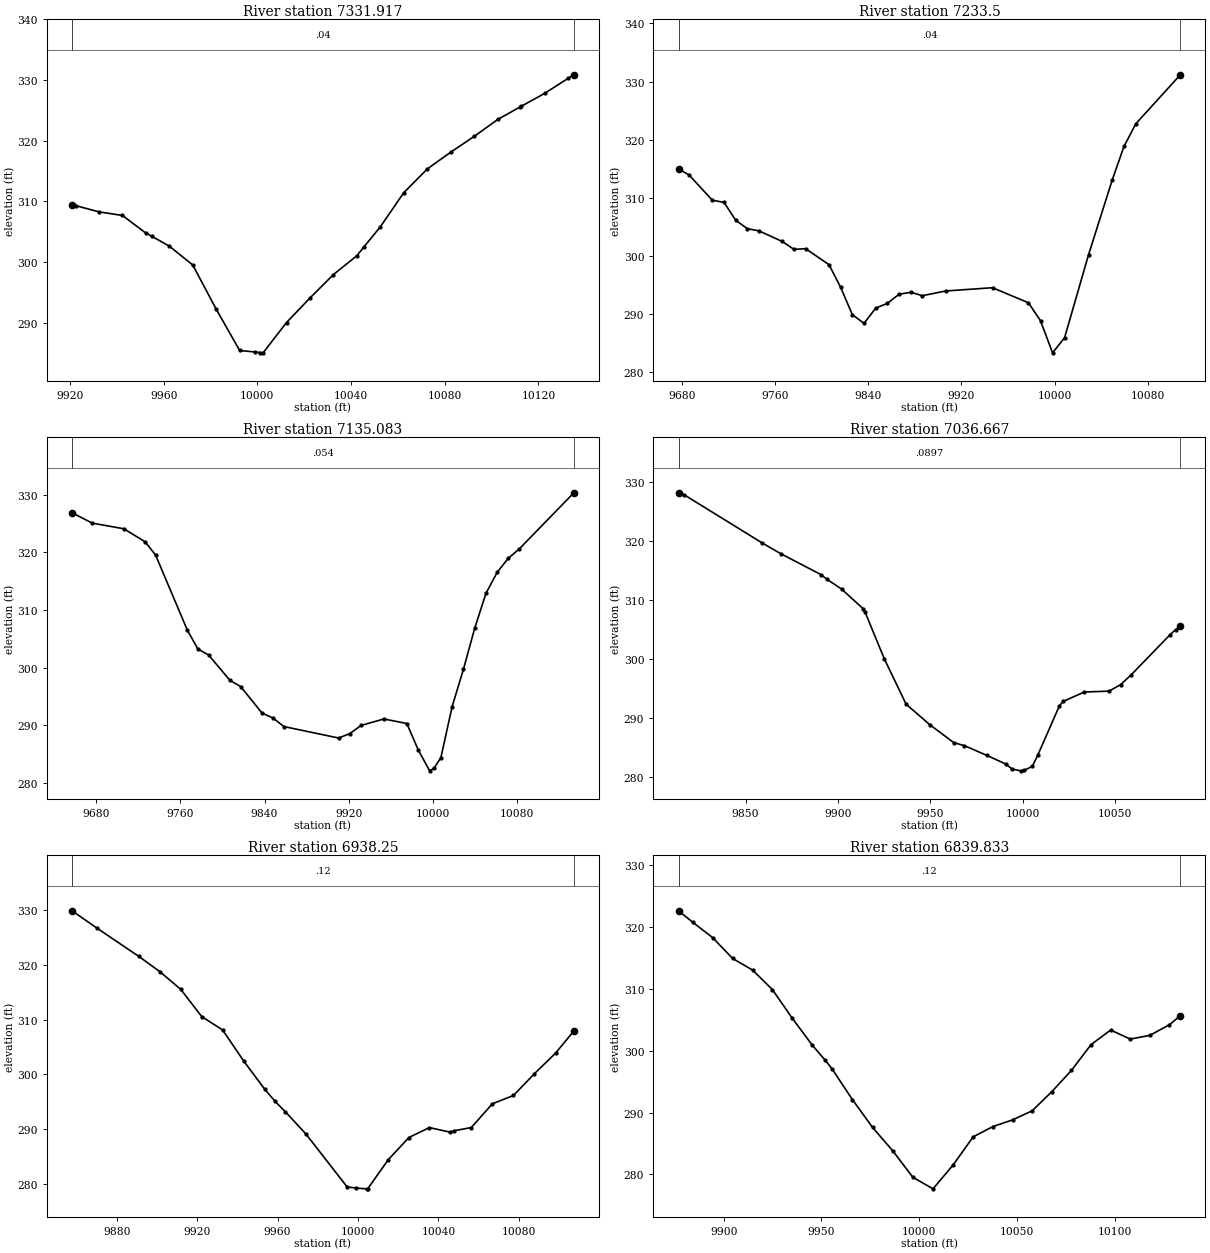
Type RM Length L Ch R = 1 ,7331.917,98.416700,98.416700,98.416700
XS GIS Cut Line= 6
822286.489240718788656.593056197822252.563628277788658.017760845
822208.438575866788656.518080084822162.037275895 788655.23642301
822095.432551315788659.884081005822072.711073036 788662.80360278
#Sta/Elev= 29
9920.894309.40619922.385309.29299932.393308.25539942.402307.66479952.411304.7456
9954.849304.23959962.417302.60489972.423299.48939982.429292.20329992.435285.3942
    9999 285.143   10001285.060710002.44 285.00610012.44290.009110022.45294.0516
10032.45297.912310042.46 301.02110045.42302.449210052.48305.7888 10062.5311.4256
10072.52315.330610082.55318.106110092.57320.7097 10102.6323.495610112.19325.5691
10112.62325.663610122.71327.815110132.79330.3103 10135.1330.8668
#Mann= 3 , 0 , 0
9920.894    0.04       09920.894    0.04       0 10135.1    0.04       0
#XS Ineff= 2 , 0
       0                               0
Bank Sta=9920.894,10135.1
Exp/Cntr=0.3,0.1

Type RM Length L Ch R = 1 ,  7233.5,98.416600,98.416600,98.416600
XS GIS Cut Line= 6
 822494.06252921788563.654332326 822299.56823554788551.270099693
822251.387492663788550.986209563822217.353292214788555.753538672
822145.897672712788574.614104265 822066.90916624788584.913003961
#Sta/Elev= 30
9676.926314.96959685.993 313.9259706.003309.57219716.007309.22049726.012 306.147
9736.017304.68879746.022304.3153 9766.06302.48569776.097301.13139786.135301.2503
9806.209   298.59816.246294.59569826.284289.89249836.321288.40889846.358291.0216
9856.396291.85159866.433293.41429876.453293.75359886.453 293.1639906.454293.9735
9946.711294.53699977.595291.94379987.957288.85289998.319283.334410008.63285.9234
10029.25300.215510049.57313.053210059.73318.854310069.89322.7387 10108.1331.1577
#Mann= 3 , 0 , 0
9676.926    0.04       09676.926    0.04       0 10108.1    0.04       0
#XS Ineff= 2 , 0
       09957.784                       0
Bank Sta=9676.926,10108.1
Exp/Cntr=0.3,0.1

Type RM Length L Ch R = 1 ,7135.083,98.416700,98.416700,98.416700
XS GIS Cut Line= 6
822514.197376335788545.305200514 822431.44950245 788540.65576495
822340.870418144788526.271699591822271.537133466788507.708156197
822128.267809452788450.695800317822055.249326248788428.379651898
#Sta/Elev= 30
9657.051326.84529676.279325.04899706.326324.06999726.357321.82699736.373319.5457
9766.597306.51369776.679 303.234 9786.81302.19469807.143297.7971 9817.31296.7182
9837.753292.10949848.105291.26929858.457289.78519910.421287.80299921.083288.5584
9931.744289.98129953.498291.10219975.296 290.3129986.195285.71829996.999282.1115
   10001282.536510007.65 284.39510018.36293.247610029.07299.690710039.78306.8081
10050.49312.868610061.15316.516110071.71318.953610082.27320.595810134.08330.3119
#Mann= 3 , 0 , 0
9657.051   0.054       09657.051   0.054       010134.08   0.054       0
#XS Ineff= 2 , 0
       09963.578                       0
Bank Sta=9657.051,10134.08
Exp/Cntr=0.3,0.1

Type RM Length L Ch R = 1 ,7036.667,98.416700,98.416700,98.416700
XS GIS Cut Line= 6
822407.789516171788491.387811664822332.018708628788465.297626677
822297.486950736788445.493755609822270.438519795788423.620580301
822215.960723487788369.272540213822182.826557521788347.164406606
#Sta/Elev= 30
9813.723328.11739816.631327.80489859.187319.60549869.114317.81599890.742 314.303
9893.966313.52369902.057311.83259913.585308.54449914.665307.99739925.113300.0749
9936.972292.37569949.833288.91149962.693285.89679968.559285.37049980.526283.7513
9990.818282.28219994.408281.4139    9999281.1207   10001281.219210005.33281.8914
10008.18283.7299 10019.9292.072910021.94 292.84310033.45294.446410046.73294.5863
10053.09295.680810058.88297.3628 10079.9 304.13610082.96305.006210085.43305.5287
#Mann= 3 , 0 , 0
9813.723  0.0897       09813.723  0.0897       010085.43  0.0897       0
#XS Ineff= 2 , 0
       0                               0
Bank Sta=9813.723,10085.43
Exp/Cntr=0.3,0.1

Type RM Length L Ch R = 1 , 6938.25,98.416600,98.416600,98.416600
XS GIS Cut Line= 6
822427.006344175788353.026650346822418.854025025788350.950292275
822326.588541027788324.005565198822288.719685959788315.736417176
822249.196476594788306.846104962822186.300308787 788287.11813443
#Sta/Elev= 27
9857.706329.85219870.133326.67489890.969321.51989901.386318.74789911.804315.5155
9922.222310.55019932.639308.10429943.057302.47759953.475297.3472 9958.69295.1006
9963.864293.18359974.104289.11189994.584279.4745    9999279.262710004.36279.1196
10004.81279.120610015.06 284.43110025.31288.481710035.56290.297410045.91289.4538
10047.68289.706910056.39290.300310066.87294.635810077.35296.149910087.83300.1406
10098.31303.871510107.43307.9201
#Mann= 3 , 0 , 0
9857.706    0.12       09857.706    0.12       010107.43    0.12       0
#XS Ineff= 2 , 0
       0                               0
Bank Sta=9857.706,10107.43
Exp/Cntr=0.3,0.1

Type RM Length L Ch R = 1 ,6839.833,98.416700,98.416700,98.416700
XS GIS Cut Line= 6
822442.169332337788248.865066959822369.444805639788235.208395449
822322.781924872788223.601461454822320.849355273788223.086510249
822291.223107737788216.160775648822189.462633245 788209.06252145
#Sta/Elev= 28
 9876.92322.65379884.214320.78599894.389318.30219904.564314.93649914.739313.0695
9924.913309.90129935.088305.24919945.263 300.9169951.779298.51189955.495297.0271
  9965.8292.10529976.105287.5952 9986.41283.81669996.714279.528910007.01277.6579
10017.28281.519810027.55 286.07310037.66287.742510047.69288.819410057.71290.2891
10067.74 293.38310077.76296.820110087.78300.990310097.81303.352910107.83301.8914
10117.86302.497410127.88304.215710133.43305.6664
#Mann= 3 , 0 , 0
 9876.92    0.12       0 9876.92    0.12       010133.43    0.12       0
#XS Ineff= 2 , 0
       0                               0
Bank Sta=9876.92,10133.43
Exp/Cntr=0.3,0.1

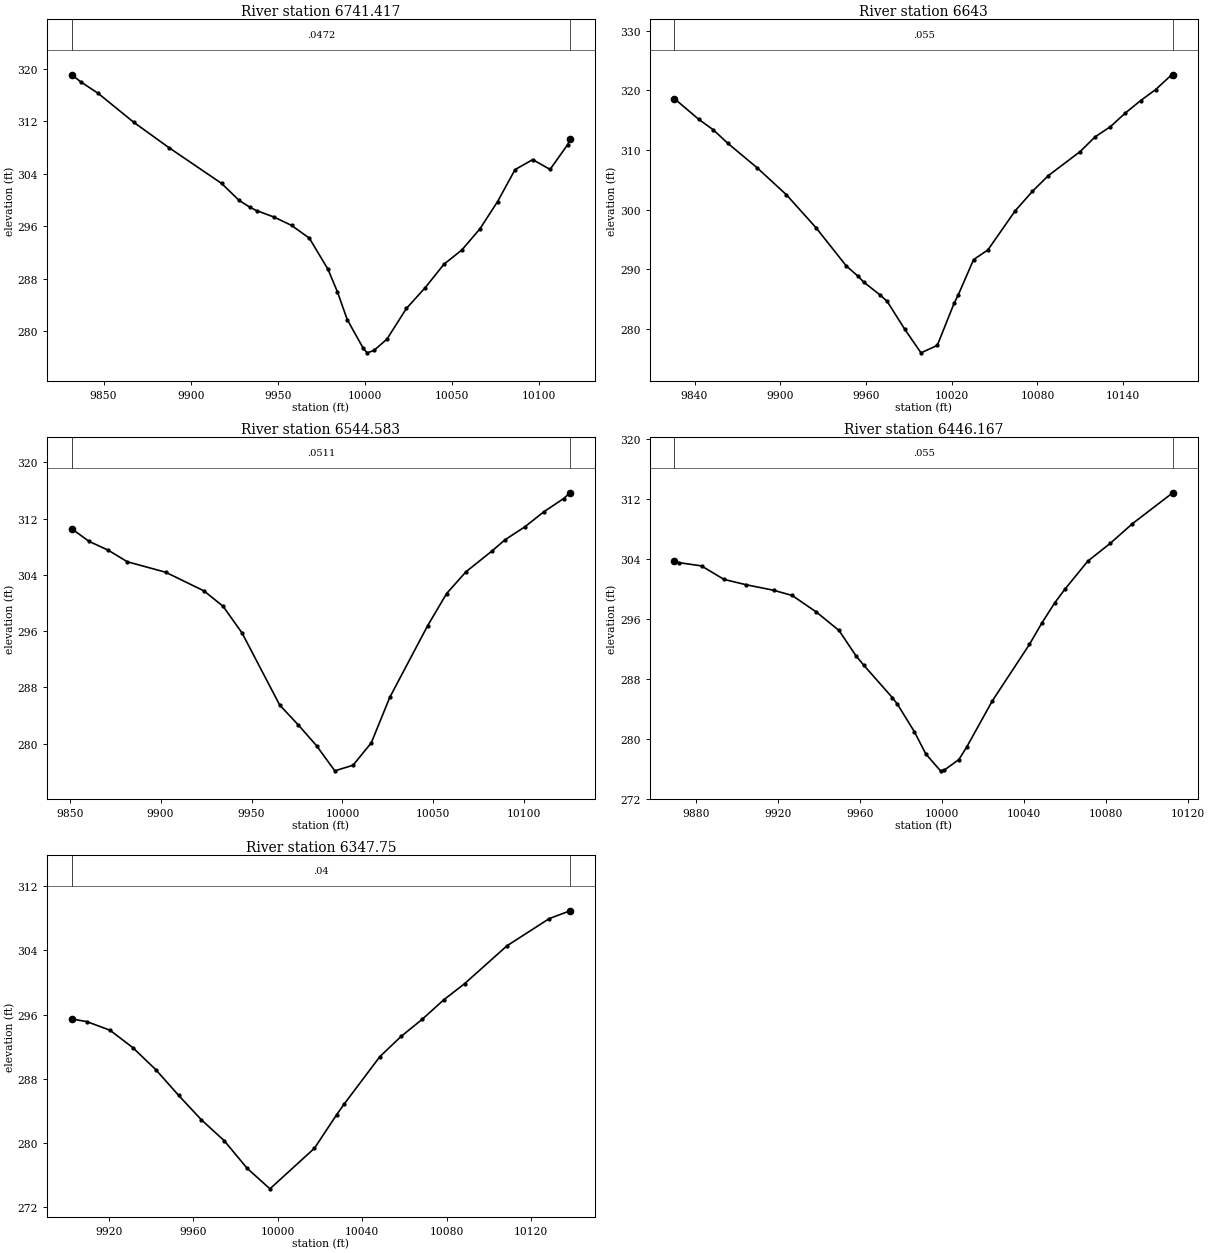
Type RM Length L Ch R = 1 ,6741.417,98.416700,98.416700,98.416700
XS GIS Cut Line= 6
822459.984108138788129.985697486822359.025554713 788115.70393949
822338.375917674788116.477691436822310.722073615788124.619552938
822258.678331728788150.337357374822183.516790822788161.212646683
#Sta/Elev= 30
9831.774319.05569836.841317.99299847.007316.20979867.338311.81479887.512 307.955
9917.711302.50579927.777299.91839933.791298.89799937.819298.35439947.826297.3725
9957.901296.09819968.109294.15549978.798289.41849984.185286.00419989.873 281.733
    9999277.397610001.26276.673410005.17277.030910012.64278.756510023.82283.4371
10034.66286.620610045.31290.162810055.66292.358810066.02295.576910076.11299.7128
10086.19304.603210096.28306.122610106.28304.632210116.28308.374710117.77309.2255
#Mann= 3 , 0 , 0
9831.774  0.0472       09831.774  0.0472       010117.77  0.0472       0
#XS Ineff= 2 , 0
       0                               0
Bank Sta=9831.774,10117.77
Exp/Cntr=0.3,0.1

Type RM Length L Ch R = 1 ,    6643,98.416600,98.416600,98.416600
XS GIS Cut Line= 6
822461.686371632788118.626362233822337.289789469788087.301602022
822321.782470178788075.754036792822280.939834814788017.661019086
822224.008225332787985.457045738822163.645984536787964.810828811
#Sta/Elev= 30
9825.955 318.5999842.978315.1365 9853.18313.37429863.382311.10799883.786307.0278
9904.325302.49869924.966296.99479946.181 290.5819954.535288.82829958.388287.8678
9969.858285.70619974.808284.63479987.264279.91779998.523276.002310009.92277.2508
10021.68284.3001 10024.7285.774910035.33291.628710045.35293.253710064.48299.8213
10076.49303.064310087.67305.712210109.82309.719210120.44312.217710131.01313.8926
10141.58316.204810152.15318.263910162.72320.120310173.29322.459210174.72322.6053
#Mann= 3 , 0 , 0
9825.955   0.055       09825.955   0.055       010174.72   0.055       0
#XS Ineff= 2 , 0
       0                               0
Bank Sta=9825.955,10174.72
Exp/Cntr=0.3,0.1

Type RM Length L Ch R = 1 ,6544.583,98.416700,98.416700,98.416700
XS GIS Cut Line= 6
822493.986170293788014.513611385822420.190691467787989.661534683
822388.286865769787980.538388281822334.269005859787974.303001282
822316.747215842 787970.85531287822231.616676559787939.400442935
#Sta/Elev= 24
9851.132310.56189860.614308.77739871.166307.52369881.717305.87259902.821304.3817
9923.925301.72359934.398299.53489944.799295.74889965.519285.49579975.671282.6969
9985.794279.71399995.822276.145410005.85276.940910015.89280.125510026.07286.6004
10046.83296.752710057.34301.357710068.01304.459610082.12307.369910089.46309.0018
10100.18310.806510110.91312.998610121.63314.847210125.26315.6841
#Mann= 3 , 0 , 0
9851.132  0.0511       09851.132  0.0511       010125.26  0.0511       0
#XS Ineff= 2 , 0
       0                               0
Bank Sta=9851.132,10125.26
Exp/Cntr=0.3,0.1

Type RM Length L Ch R = 1 ,6446.167,98.416600,98.416600,98.416600
XS GIS Cut Line= 6
822507.140414714787954.497371184822464.993484262787936.107555395
822434.501376927787919.376603527822349.608760428787858.416976775
822319.733283332787844.625249595822296.317152311787837.046411603
#Sta/Elev= 28
 9869.53303.67079871.811303.47719882.736303.04469893.662301.24469904.587300.5267
9917.822299.79899926.919299.1015 9938.61296.91019949.732294.43819958.067291.0343
9961.802289.80739975.812285.45379978.205284.60569986.449280.94389992.094277.9456
9999.236275.7059   10001275.7966 10008.2 277.21510011.95278.857310024.46285.0276
10042.57292.572110048.55 295.38810054.92298.1249   10060299.983810071.01303.6783
10082.02306.0671 10092.8 308.68210112.44312.8003
#Mann= 3 , 0 , 0
 9869.53   0.055       0 9869.53   0.055       010112.44   0.055       0
#XS Ineff= 2 , 0
       0                               0
Bank Sta=9869.53,10112.44
Exp/Cntr=0.3,0.1

Type RM Length L Ch R = 1 , 6347.75,98.416700,98.416700,98.416700
XS GIS Cut Line= 6
822531.873001064787841.654945908822442.746833141787805.333555705
 822411.62560887787795.435639374822388.591415626787790.916410946
822363.619629268787789.300717448822305.101414016787788.269765608
#Sta/Elev= 21
9902.522295.45499909.809295.10499920.626294.04399931.443291.87329942.261 289.144
9953.078285.93569963.896282.87779974.713280.27279985.531276.84149996.348 274.273
10017.41  279.33 10027.9283.501510031.44284.825310048.39290.752110058.52293.2902
10068.54295.428710078.56297.818110088.56  299.8610108.56304.567810128.57307.9585
10138.47308.9377
#Mann= 3 , 0 , 0
9902.522    0.04       09902.522    0.04       010138.47    0.04       0
#XS Ineff= 2 , 0
       0                               0
Bank Sta=9902.522,10138.47
Exp/Cntr=0.3,0.1