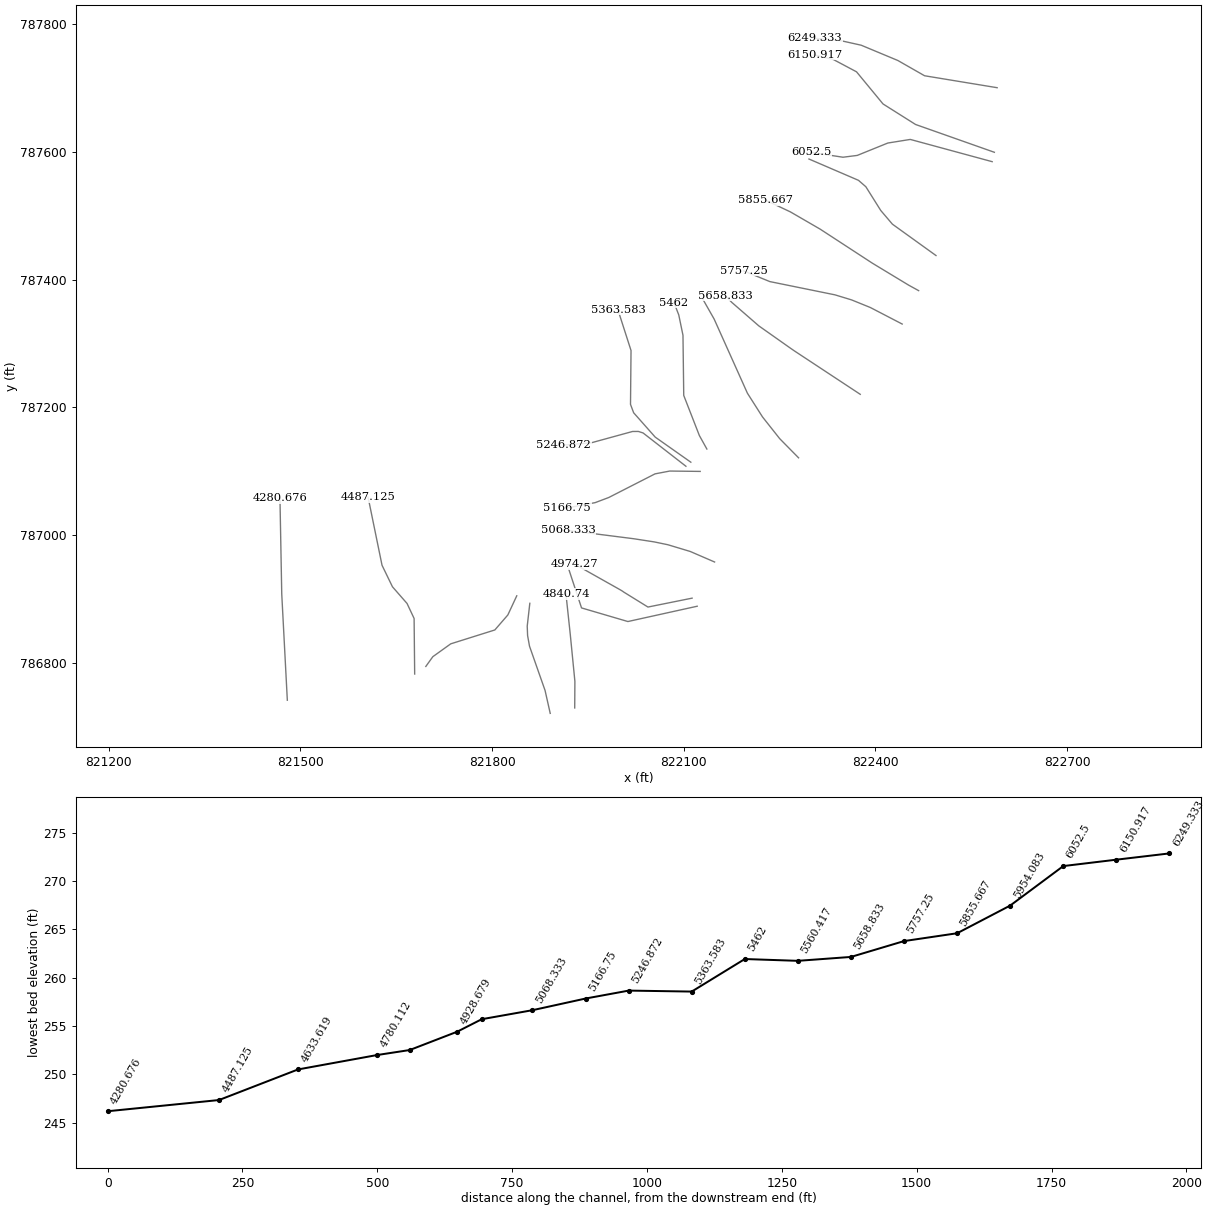
HEC-RAS study 17397_ras.prj: 17397

--- 17397_ras.g01 (geometry) --- (continued)

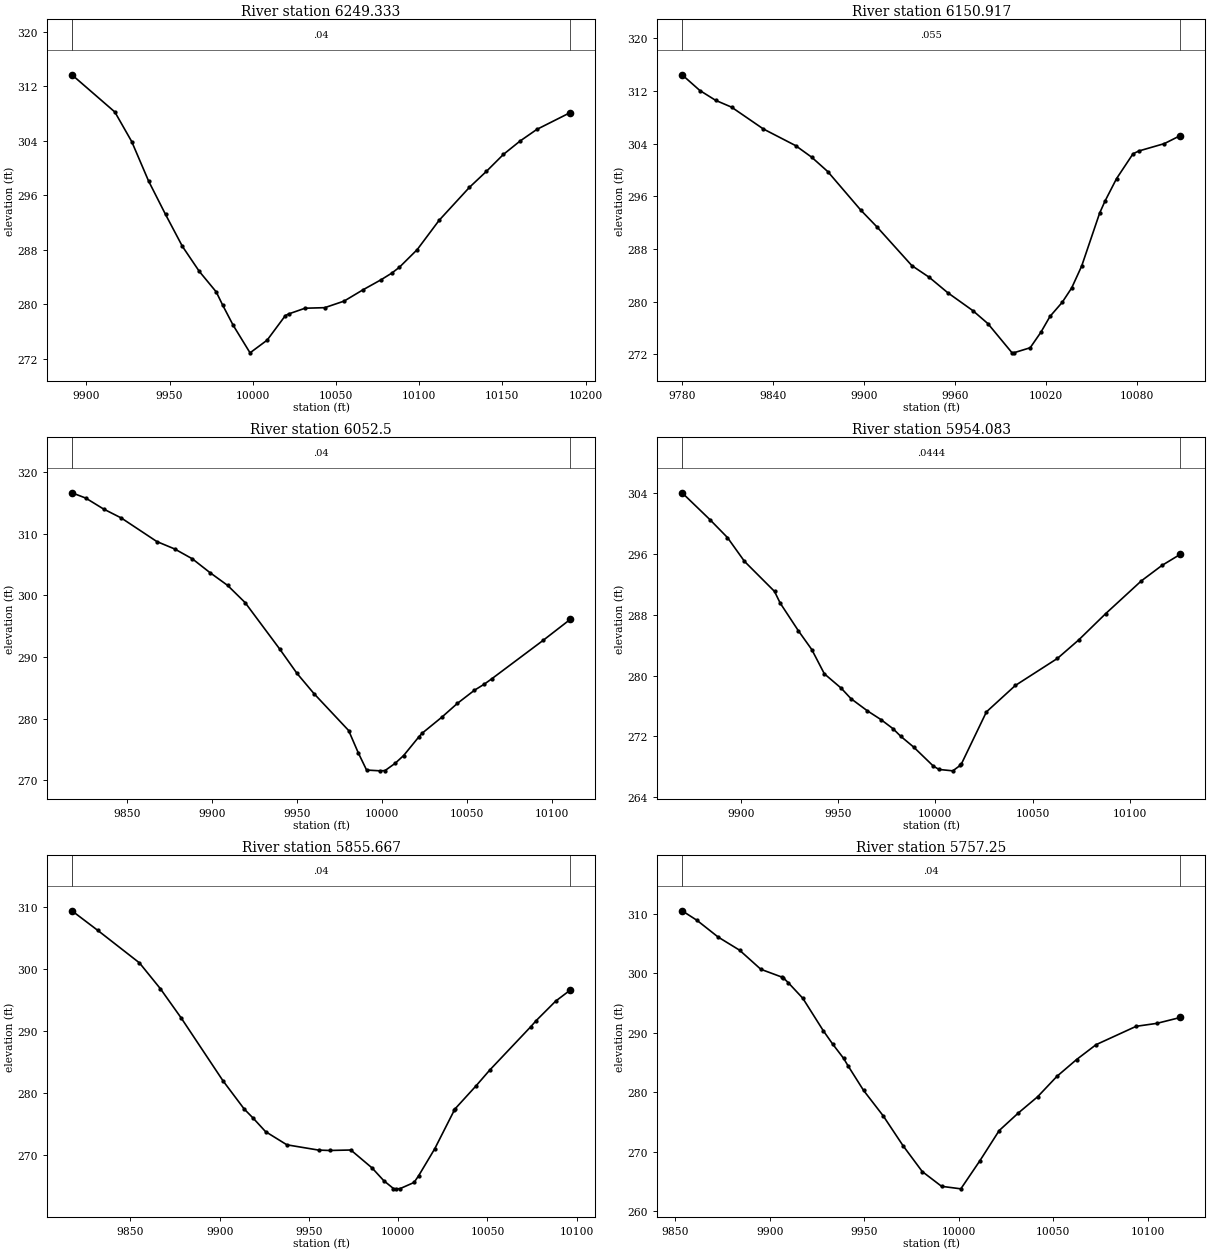
Type RM Length L Ch R = 1 ,6249.333,98.416700,98.416700,98.416700
XS GIS Cut Line= 6
822590.572470455787700.179296538822477.007873293787718.875947643
822435.141185767787742.780398863 822377.82009266787766.684522785
822344.739238543787774.066297231822304.965280007787777.447111767
#Sta/Elev= 29
9891.269313.71369917.081308.24819927.214303.90629937.376298.09869947.537293.2029
9957.698288.5055 9967.86284.82839978.021281.82029981.823279.91389988.182 276.928
9998.343 272.86810008.62274.731110019.57278.3396 10021.5278.576710031.39279.4221
10043.21 279.50210054.86280.465510066.06 282.10210077.11283.6054 10083.6284.5876
10088.16285.448410098.83288.030810111.98 292.32910130.18297.169910140.42299.5253
10150.67302.020810160.71303.990310170.75305.692610190.85308.1639
#Mann= 3 , 0 , 0
9891.269    0.04       09891.269    0.04       010190.85    0.04       0
#XS Ineff= 2 , 0
       0                               0
Bank Sta=9891.269,10190.85
Exp/Cntr=0.3,0.1

Type RM Length L Ch R = 1 ,6150.917,98.416600,98.416600,98.416600
XS GIS Cut Line= 6
822586.224512538787599.103457045822462.910097258787642.617826935
822411.970323204787674.751032293822370.490966721787725.045241265
822334.364754714787744.239351425822304.639399464787751.539608192
#Sta/Elev= 30
9780.111314.44159791.823312.05229802.256310.5565 9812.69309.52879833.666 306.213
9854.876303.69079865.481301.93139876.086299.74839897.843293.89579908.739291.2913
9931.518285.46389942.966283.69089955.178 281.3489971.703278.63069981.601276.6635
9997.544272.22249998.583272.2188 10009.5272.991210016.52275.333510022.57 277.755
10030.56279.877310036.82 282.065 10043.4285.378510055.27293.4375 10058.8295.2558
10066.41298.676210077.26302.441410081.13302.872110097.89303.987410108.55305.2197
#Mann= 3 , 0 , 0
9780.111   0.055       09780.111   0.055       010108.55   0.055       0
#XS Ineff= 2 , 0
       0                               0
Bank Sta=9780.111,10108.55
Exp/Cntr=0.3,0.1

Type RM Length L Ch R = 1 ,  6052.5,98.416700,98.416700,98.416700
XS GIS Cut Line= 6
822582.777078509787584.427237867822454.639543713787619.228647387
822419.489984078787613.595273492822371.581706447787594.199857778
822349.319024971787591.375550603822299.247466999787599.004349911
#Sta/Elev= 29
9817.294316.62769825.443  315.779835.921314.00239846.399312.54249867.355308.7222
9877.833307.52459888.285 305.9229898.649 303.6899909.012301.62579919.375298.8296
9939.848291.26559949.935287.35779959.954284.07729980.381278.0947 9986.09274.4603
9990.957271.6863    9999271.557710001.84271.601310007.77272.7704 10012.8274.0391
10021.79277.072410023.69277.651510035.28280.249110044.46282.489110054.54284.6257
10060.27285.5985 10064.6 286.44710094.94292.691910111.02296.1151
#Mann= 3 , 0 , 0
9817.294    0.04       09817.294    0.04       010111.02    0.04       0
#XS Ineff= 2 , 0
       0                               0
Bank Sta=9817.294,10111.02
Exp/Cntr=0.3,0.1

Type RM Length L Ch R = 1 ,5954.083,98.416700,98.416700,98.416700
XS GIS Cut Line= 6
822494.873038366787437.516774524822426.650433082787486.619254236
 822408.42578833787508.018546555822385.104553984787545.176541924
 822373.52956486787555.234186133822296.049228811787588.575312349
#Sta/Elev= 29
9869.821304.06049884.128300.52769893.138298.17089901.896295.03489917.335291.0817
9920.236289.55059929.652285.88269936.476283.43489942.963280.23489951.625278.3462
9956.624276.97079965.086275.36499972.047274.21469978.222273.02249982.186272.0248
9988.828270.6061    9999268.089910001.89267.6523   10009267.469710012.73 268.176
10013.38268.363510026.28275.229110041.12278.701510062.77282.261610073.67284.6855
10087.54288.1473 10105.9292.464310116.53294.502910126.04295.9782
#Mann= 3 , 0 , 0
9869.821  0.0444       09869.821  0.0444       010126.04  0.0444       0
#XS Ineff= 2 , 0
       0                               0
Bank Sta=9869.821,10126.04
Exp/Cntr=0.3,0.1

Type RM Length L Ch R = 1 ,5855.667,98.416600,98.416600,98.416600
XS GIS Cut Line= 6
822467.738235127787382.551403886822452.261205316787391.059411202
822395.341645364787425.501384208822313.587804512 787478.82020222
822267.007216809787505.810874637822227.623716619787524.426840083
#Sta/Elev= 29
9817.205309.39759831.741306.22859855.041301.00519866.729296.85819878.418292.1354
9901.803282.02449913.746277.45199918.769 275.9859925.688273.81889937.631271.6952
9955.352270.84669961.517270.78379973.459270.85929985.402267.95719991.935265.9087
9997.345264.6497    9999 264.603   10001264.631110008.88265.631410011.45266.7198
10020.45271.053810031.34 277.22610032.02277.543610043.59 281.19110051.22283.7215
10074.34290.749310077.18291.674110088.24294.8555 10096.4 296.627
#Mann= 3 , 0 , 0
9817.205    0.04       09817.205    0.04       0 10096.4    0.04       0
#XS Ineff= 2 , 0
       0                               0
Bank Sta=9817.205,10096.4
Exp/Cntr=0.3,0.1

Type RM Length L Ch R = 1 , 5757.25,98.416700,98.416700,98.416700
XS GIS Cut Line= 6
822441.944306664787330.302164203822392.078963167787356.191141098
822362.825888588787368.053729881 822336.72125115787375.998609932
822234.822542412787396.735723999 822193.70771778787413.512357392
#Sta/Elev= 29
9853.699310.51749861.523308.9238 9872.79306.09689884.058303.90399895.325 300.688
9906.593299.35969907.299299.23049909.884298.42039917.523295.81979928.314 290.386
9933.325288.11899939.105 285.7189941.451 284.4659949.631280.34639960.084276.0392
9970.494271.05739980.699266.69289990.904264.216310001.09263.792210011.23268.5453
10021.38273.591610031.52276.544610041.67279.257710051.98282.719210062.29285.5186
 10072.6288.0178 10093.8291.102810104.75   291.610117.24292.5946
#Mann= 3 , 0 , 0
9853.699    0.04       09853.699    0.04       010117.24    0.04       0
#XS Ineff= 2 , 0
       0                               0
Bank Sta=9853.699,10117.24
Exp/Cntr=0.3,0.1

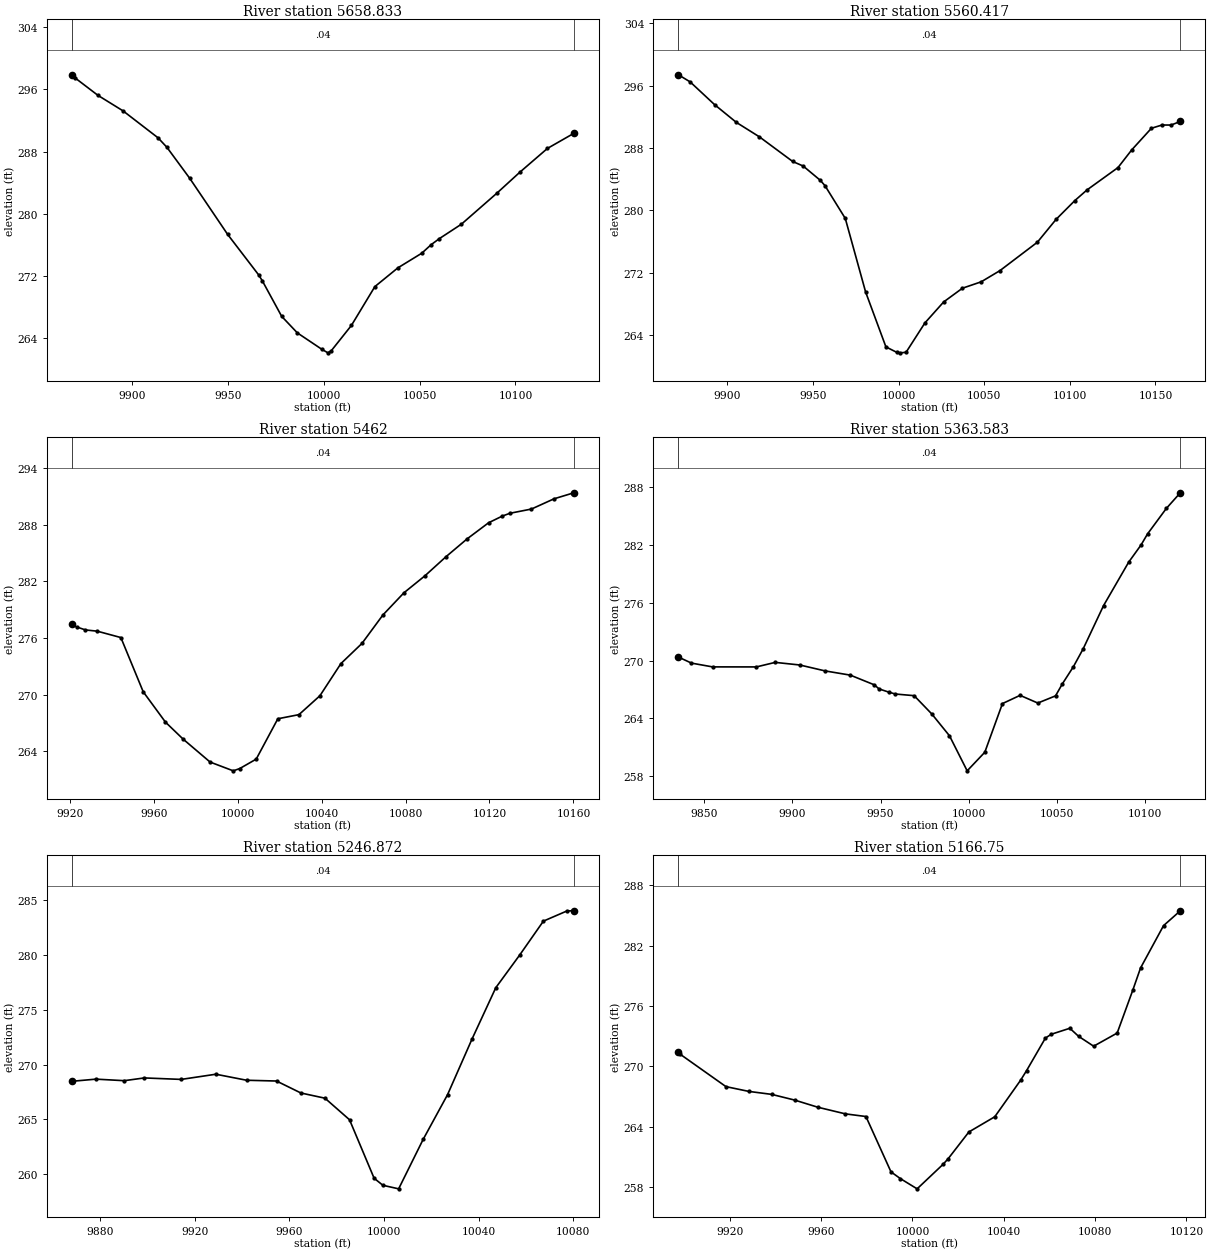
Type RM Length L Ch R = 1 ,5658.833,98.416700,98.416700,98.416700
XS GIS Cut Line= 6
822376.309662528787220.314809273822272.608265196787288.689050316
822267.648597003787292.103600405822217.539795126787327.454458129
822175.080482974787364.371624868822165.385437221 787374.31548131
#Sta/Elev= 26
9868.765297.86889870.334297.47639882.312295.22719895.443293.2265 9913.61289.7803
9918.246288.56459930.224284.55449949.943277.36529966.158272.1502 9968.11 271.369
9978.136266.83579986.277264.7186    9999262.616810002.24262.151110004.03262.4312
10014.48265.668510026.72270.658810038.72273.067310051.19274.949810056.07276.0444
10060.32276.818410071.82278.671210090.19282.6264 10102.3285.3492 10116.7288.4078
10130.48290.3491
#Mann= 3 , 0 , 0
9868.765    0.04       09868.765    0.04       010130.48    0.04       0
#XS Ineff= 2 , 0
       0                               0
Bank Sta=9868.765,10130.48
Exp/Cntr=0.3,0.1

Type RM Length L Ch R = 1 ,5560.417,98.416600,98.416600,98.416600
XS GIS Cut Line= 6
822279.808736852787120.904307914822250.240402337787150.936009796
822223.394821817787184.865035674822199.716812467787222.072858528
822147.693652066787338.023480847822129.703456224787369.671159973
#Sta/Elev= 30
9871.487 297.3759878.341296.46299892.594293.55079905.301291.27639918.814289.4167
9938.194286.26679944.317285.6834 9954.31283.85479957.057283.16939968.916278.9668
9980.776269.54819992.635262.5097    9999261.8073   10001261.747110004.39261.8145
10015.42 265.58610026.36268.2702 10037.3270.026810048.24270.845310059.18 272.277
10081.06275.920110091.99278.849610102.93281.255110110.09282.629610128.12285.4831
10136.14287.747410147.65290.5217 10153.8290.937410159.15 290.93510164.52291.3968
#Mann= 3 , 0 , 0
9871.487    0.04       09871.487    0.04       010164.52    0.04       0
#XS Ineff= 2 , 0
       0                               0
Bank Sta=9871.487,10164.52
Exp/Cntr=0.3,0.1

Type RM Length L Ch R = 1 ,    5462,98.416700,98.416700,98.416700
XS GIS Cut Line= 6
822136.277817151 787134.67392304822124.528095067 787155.79759855
822100.070584993787218.572889846822098.885177474787312.673617442
822092.291807184 787344.56861111822084.815068799787363.828544467
#Sta/Elev= 28
9921.031277.42249923.291277.15829927.481276.84329933.106276.71149944.344276.0375
9954.992270.2998 9965.59267.0898 9974.03265.28669986.866262.86319997.905261.9342
   10001262.177110008.84263.174810019.15267.4444 10029.2267.880510039.21 269.882
10049.21273.283910059.22275.413710069.23278.429810079.24 280.77510089.26282.5741
10099.29284.594110109.36286.482810119.57288.183110126.17288.896910129.78289.1903
10140.01289.636210150.74290.717610160.21291.3572
#Mann= 3 , 0 , 0
9921.031    0.04       09921.031    0.04       010160.21    0.04       0
#XS Ineff= 2 , 0
       0                               0
Bank Sta=9921.031,10160.21
Exp/Cntr=0.3,0.1

Type RM Length L Ch R = 1 ,5363.583,116.711000,116.711000,116.711000
XS GIS Cut Line= 6
822111.194097039787114.049530945822055.387217863787153.362697897
822021.678732289787191.439030833822016.756550823787204.580954154
 822017.58096078787288.846520765821997.148487358787352.417973548
#Sta/Elev= 30
9835.336270.36169842.748269.73269854.714269.34199879.551269.33849890.246 269.809
9904.219269.5382 9918.54 268.925 9932.86268.48699946.494267.47939949.144267.0591
9954.605266.73019958.408266.52919969.059266.35849979.087264.45949989.115262.1972
9999.142258.565110009.15260.494810019.15265.537210029.16266.391410039.21265.5932
10049.27266.337910053.13267.578810059.44269.372410064.99271.2298 10076.5275.6917
10090.76280.198210097.77281.977410101.45283.122710112.13285.770810120.06287.3927
#Mann= 3 , 0 , 0
9835.336    0.04       09835.336    0.04       010120.06    0.04       0
#XS Ineff= 2 , 0
       09969.551         10019.6       0
Bank Sta=9835.336,10120.06
Exp/Cntr=0.3,0.1

Type RM Length L Ch R = 1 ,5246.872,80.122300,80.122300,80.122300
XS GIS Cut Line= 6
822103.495466719787107.719546015822036.423718221787159.841537175
822029.081256422787162.198300493 822019.94612348787162.149404921
821955.362284995787144.434118693821912.106810064787140.904075524
#Sta/Elev= 22
9867.965268.47929878.131268.67519890.098268.53449898.574268.78559914.201268.6511
9928.848269.12329941.861 268.5749954.517 268.5039964.814267.4124 9975.01266.9363
9985.405264.96899995.801 259.635 9999.51258.991110006.18258.666710016.53  263.17
10026.87 267.25710037.21272.325110047.29277.019910057.37279.991610067.42283.0909
10077.42284.022310080.31 284.036
#Mann= 3 , 0 , 0
9867.965    0.04       09867.965    0.04       010080.31    0.04       0
#XS Ineff= 2 , 0
       0                               0
Bank Sta=9867.965,10080.31
Exp/Cntr=0.3,0.1

Type RM Length L Ch R = 1 , 5166.75,98.416700,98.416700,98.416700
XS GIS Cut Line= 6
822125.824632972787099.648107529822078.163318276787100.220178887
822055.161779046787095.814919233821982.696761608787058.805706307
821961.413460553787050.775874287821917.699174404787042.544255272
#Sta/Elev= 28
9897.488 271.4549898.313271.20229918.314267.99299928.315267.51929938.315267.2252
9948.373266.65989958.555265.94769970.649265.2871 9979.62265.02579990.599259.5275
9994.687258.862910002.04257.844310013.37260.271310015.66260.842110024.71263.4914
10036.05265.001110047.39268.6358   10050269.591210058.23272.814610060.79273.1927
10068.92273.787910072.75272.991410079.36272.007710089.66273.3123 10096.5277.5694
10099.89279.769110109.97283.978410117.32285.4542
#Mann= 3 , 0 , 0
9897.488    0.04       09897.488    0.04       010117.32    0.04       0
#XS Ineff= 2 , 0
       0                               0
Bank Sta=9897.488,10117.32
Exp/Cntr=0.3,0.1

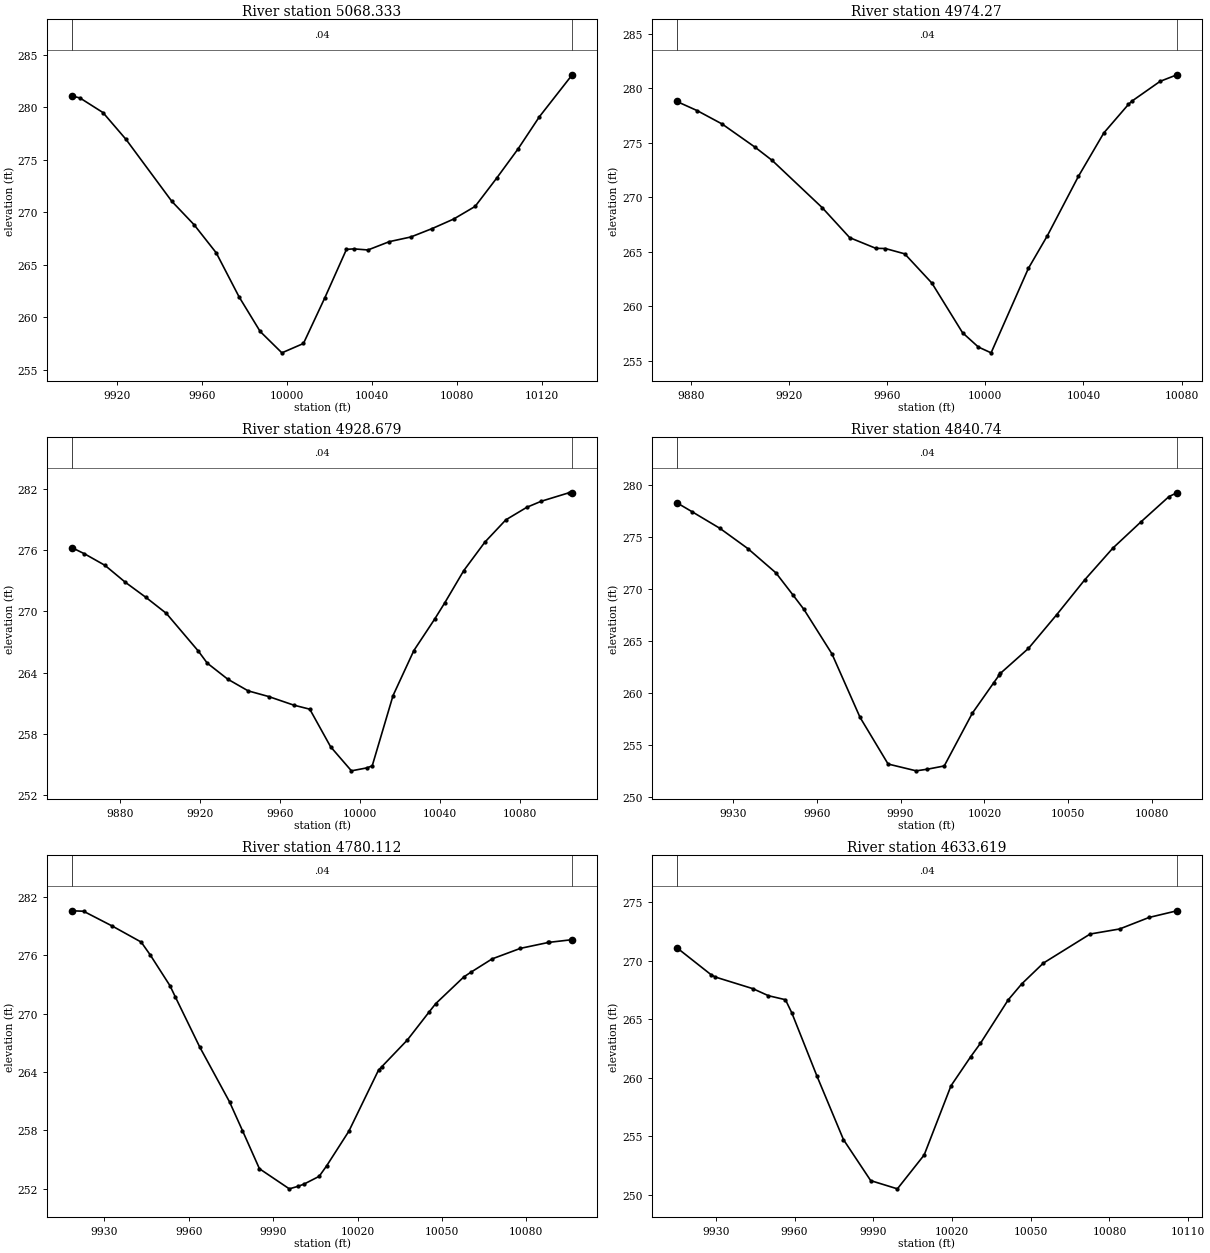
Type RM Length L Ch R = 1 ,5068.333,94.063000,94.063000,94.063000
XS GIS Cut Line= 6
822148.356477722786957.886077641822110.156546368786974.384111698
 822075.27670498786984.885041391822053.684420568786989.365322958
822021.616392888786994.311708849821919.704436978 787007.27522549
#Sta/Elev= 24
9898.899281.05989902.654280.88239913.522 279.488 9924.39276.92899945.907271.0441
 9956.35268.82579966.793266.14489977.514261.96399987.443258.66959997.656256.6373
10007.79257.526910017.91261.900110028.02266.477710031.45266.525310038.12266.4209
 10048.2267.213410058.28267.655510068.36268.458510078.44269.362710088.52270.5628
 10098.6273.238510108.68276.022710118.76279.096110134.18283.0818
#Mann= 3 , 0 , 0
9898.899    0.04       09898.899    0.04       010134.18    0.04       0
#XS Ineff= 2 , 0
       0                               0
Bank Sta=9898.899,10134.18
Exp/Cntr=0.3,0.1

Type RM Length L Ch R = 1 , 4974.27,45.591600,45.591600,45.591600
XS GIS Cut Line= 6
822113.178587208786901.304863676822044.054341296786887.376736179
 822005.96983237786910.944249645822004.358530322 786912.12903057
822001.249453167786914.035780385821929.011895368786954.704579174
#Sta/Elev= 22
9874.284278.78299882.627277.93739892.828276.70429906.203274.5828 9913.23273.3603
9933.632269.02029944.797266.27479955.445265.29499959.284265.27969967.205264.7907
9978.288262.10249990.788257.54489997.197256.2397 10002.4255.704210017.58263.4521
10025.35266.464110037.96271.897210048.31275.882810058.35278.505410059.78278.8077
10071.26280.621610078.13281.2237
#Mann= 3 , 0 , 0
9874.284    0.04       09874.284    0.04       010078.13    0.04       0
#XS Ineff= 2 , 0
       0                               0
Bank Sta=9874.284,10078.13
Exp/Cntr=0.3,0.1

Type RM Length L Ch R = 1 ,4928.679,87.938900,87.938900,87.938900
XS GIS Cut Line= 4
822121.165563464786888.658817947822012.675802529786864.697889134
 821940.12743485 786885.99649252821920.159994185786946.564395845
#Sta/Elev= 28
9855.902276.22539862.216275.62339872.457274.49649882.698272.83529892.939271.3688
 9903.18 269.8029919.236266.10759923.662264.93919933.903263.37359944.144262.2262
9954.385261.67379967.006260.83089975.006260.43449985.428256.7623 9995.85254.4091
10003.58254.697310006.27254.901310016.69261.767710027.12266.170210037.54269.2459
10042.62270.8433 10052.1273.983110062.63276.755810073.15278.940810083.68280.1715
10090.93280.762210104.74281.587310106.39281.5855
#Mann= 3 , 0 , 0
9855.902    0.04       09855.902    0.04       010106.39    0.04       0
#XS Ineff= 2 , 0
       0                               0
Bank Sta=9855.902,10106.39
Exp/Cntr=0.3,0.1

Type RM Length L Ch R = 1 , 4840.74,60.627600,60.627600,60.627600
XS GIS Cut Line= 5
821929.439960895786729.478290588821929.721700599786771.132385752
821922.679619773786842.569465106821922.482125981 786844.55969027
821915.729836498786907.843067876
#Sta/Elev= 24
9909.847278.27559915.369277.40369925.369275.80139935.369273.85629945.369271.5341
9951.502269.39949955.388268.02819965.437263.74849975.485257.65449985.534253.1678
9995.582252.51379999.633252.672210005.63252.983510015.68258.048310023.29 260.956
10025.29261.710810025.73261.877910035.78264.277110045.84267.4994 10055.9270.8575
10065.96273.901510076.01276.422310086.07278.859510088.93279.2224
#Mann= 3 , 0 , 0
9909.847    0.04       09909.847    0.04       010088.93    0.04       0
#XS Ineff= 2 , 0
       0                               0
Bank Sta=9909.847,10088.93
Exp/Cntr=0.3,0.1

Type RM Length L Ch R = 1 ,4780.112,146.493500,146.493500,146.493500
XS GIS Cut Line= 6
821891.112888721786720.963115079821883.037191092786756.846312334
821858.686446761786826.131687687 821855.70750565786842.751472805
821855.116825948786857.487173175821859.175718184786893.270565536
#Sta/Elev= 29
9918.436280.59229922.574280.54589932.824279.01779943.074277.37499946.277276.0601
9953.324 272.8819955.217271.73269963.876266.59059974.496260.9345 9979.09257.9827
9985.116254.06349995.736251.9943    9999252.2666   10001252.487110006.35253.2792
10008.99254.350210016.91257.921210027.47264.213410028.66264.568710037.67267.2914
10045.55270.2249 10047.8271.0448 10057.8 273.79410060.29  274.2710067.84275.6434
10077.89276.726610087.81277.332410087.93277.340310096.32277.6214
#Mann= 3 , 0 , 0
9918.436    0.04       09918.436    0.04       010096.32    0.04       0
#XS Ineff= 2 , 0
       0                               0
Bank Sta=9918.436,10096.32
Exp/Cntr=0.3,0.1

Type RM Length L Ch R = 1 ,4633.619,146.493500,146.493500,146.493500
XS GIS Cut Line= 6
821696.414914581786794.412750545  821707.3660088786809.664770149
821735.449205349786829.813900784 821804.41968558786851.503358758
 821824.78785934786874.989841303821838.739487233786904.948411785
#Sta/Elev= 22
9915.043271.11849928.076268.81459929.762 268.6029944.118267.60439950.027267.0047
9956.515266.66179958.944265.53469968.578260.10449978.633254.70529989.008251.2057
9999.168250.503710009.38253.396310019.61259.310210027.14261.800610030.82262.9353
 10041.4266.646110046.55268.0107 10054.8269.789510072.64272.275110083.87272.7062
10095.08273.689710105.73274.2608
#Mann= 3 , 0 , 0
9915.043    0.04       09915.043    0.04       010105.73    0.04       0
#XS Ineff= 2 , 0
       0                               0
Bank Sta=9915.043,10105.73
Exp/Cntr=0.3,0.1

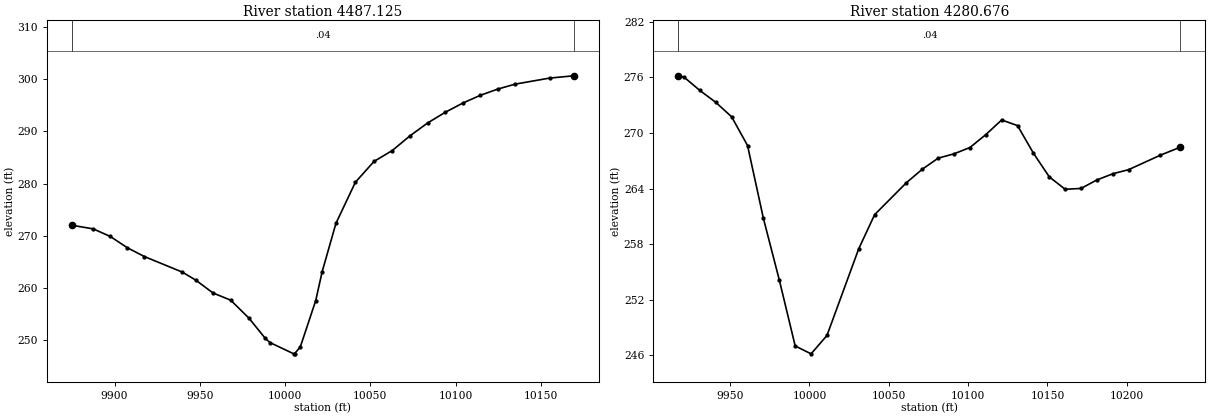
Type RM Length L Ch R = 1 ,4487.125,206.449300,206.449300,206.449300
XS GIS Cut Line= 6
821678.967942476786782.548838332821678.084159493786869.476871178
821667.042208761786892.963830441821644.214201152786919.073306724
821627.885309517786952.740155131821606.079606235787059.203341663
#Sta/Elev= 30
9875.054271.99099887.506271.29889897.506269.83999907.507267.67459917.516265.9909
9939.767263.00459947.622261.47249957.707259.01429968.102  257.639978.814254.1831
9988.337250.32789991.158249.498110005.13247.336510005.62247.386410008.93248.6424
   10018257.554810021.78263.099910029.86272.365210041.27280.247210052.17284.2309
10062.91286.330810073.32289.152610083.72291.630210094.12293.685510104.51295.4636
10114.64296.923410124.77298.1099 10134.9299.053510155.15300.218210169.47300.6628
#Mann= 3 , 0 , 0
9875.054    0.04       09875.054    0.04       010169.47    0.04       0
#XS Ineff= 2 , 0
       0                               0
Bank Sta=9875.054,10169.47
Exp/Cntr=0.3,0.1

Type RM Length L Ch R = 1 ,4280.676,0.000000,0.000000,0.000000
XS GIS Cut Line= 3
821479.664397865786741.532312303821470.929589517786907.944319081
821468.132446147787057.591489252
#Sta/Elev= 30
9917.428 276.1629920.901276.02359930.915274.57589940.928273.29979950.942271.7361
9960.956268.6415 9970.97260.77659980.983254.13889990.997247.025910001.01246.1777
10011.02248.158410031.05257.512110041.07261.187310061.09 264.63110071.11266.0883
10081.12 267.27810091.13267.748710101.13268.425710111.13269.816110121.13271.3948
10131.13270.790410141.14267.818310151.14265.261410161.14263.924910171.14264.0118
10181.14264.927810191.14 265.59310201.15 266.03810221.15267.599710233.74268.4613
#Mann= 3 , 0 , 0
9917.428    0.04       09917.428    0.04       010233.74    0.04       0
#XS Ineff= 2 , 0
       0                               0
Bank Sta=9917.428,10233.74
Exp/Cntr=0.3,0.1